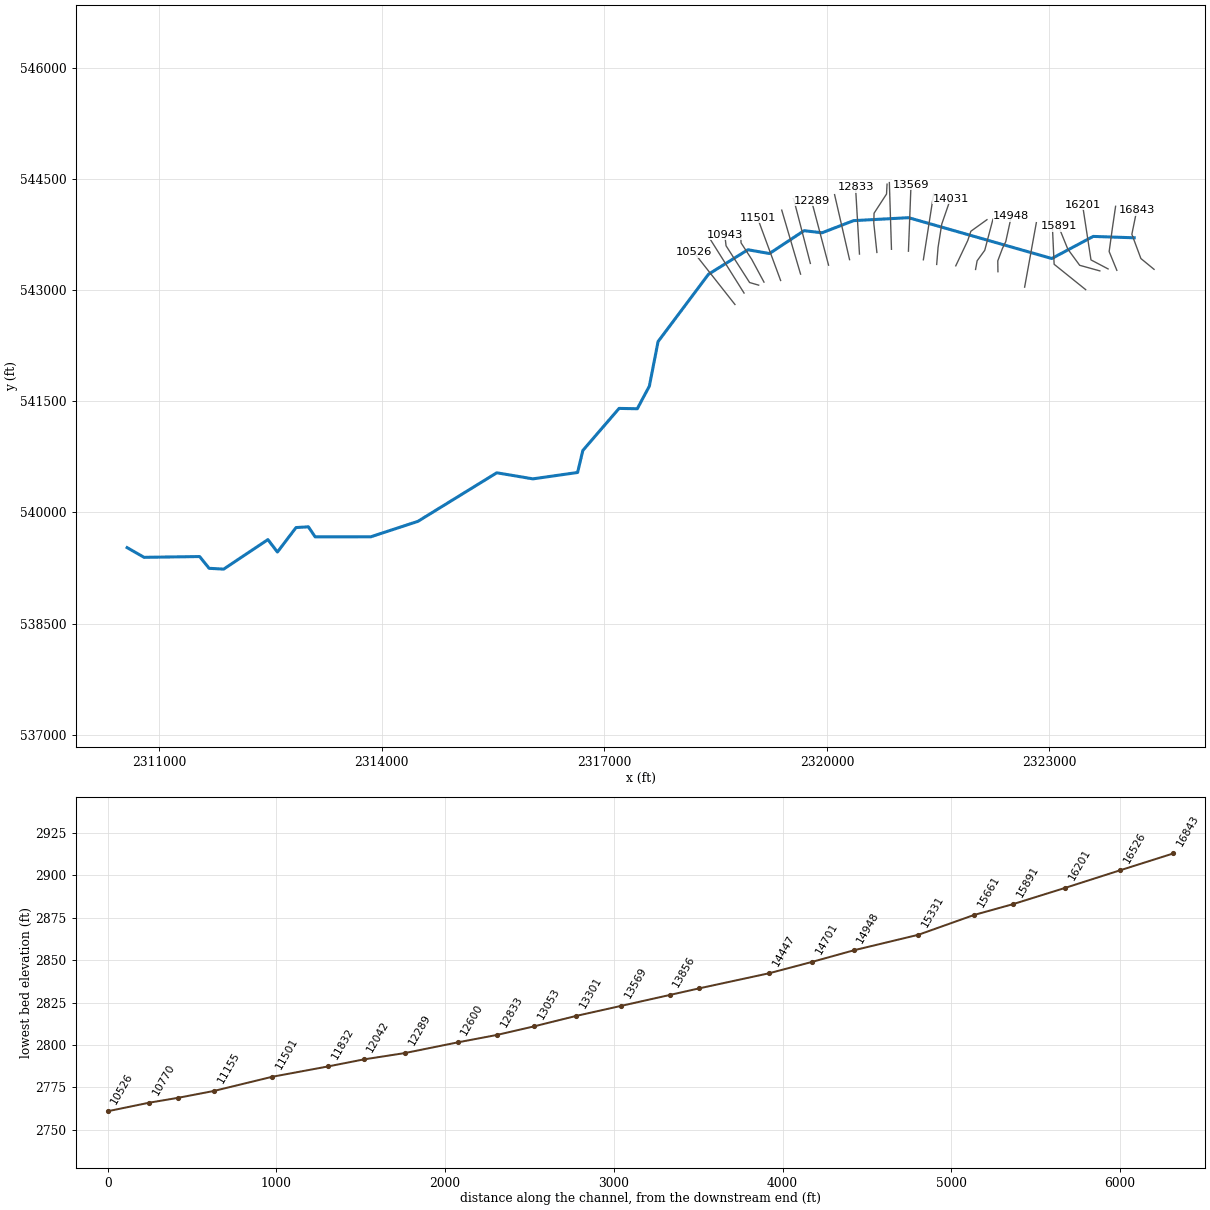
--- SLSBRYRN.prj (project) ---

Proj Title=SLSBRYRN
Current Plan=p01
Default Exp/Contr=0,0
English Units
Geom File=g01
Flow File=f01
Plan File=p01
Background Map Layer=Inundation Boundary (01pct Value_0)
Background Map Layer=Inundation Boundary (01pct Value_0)
BEGIN DESCRIPTION:
----------MODEL BY WOOD PLC 2021----------
Stream Name: Saulsbury Run
Flood Zone: Enhanced Approximate
Pocahontas County, WV
HEC-RAS Version: RAS 6.1
Vertical Datum: NAVD88
Projection: NAD 1983 StatePlane West Virginia S FIPS 4702 (US Feet)
Terrain: 1-meter LIDAR (FEMA Region III 3DEP collected 2016-2018)
Land Use: 2019 NLCD
Hydrologic Method:
WV SIR2010-5033 regression equations
Model Notes:
Normal depth tie in with Deer Creek
END DESCRIPTION:
DSS Export Rating Curves= 0
DSS Export Rating Curve Sorted= 0
DSS Export Volume Flow Curves= 0
DXF OffsetX= 0
DXF OffsetY= 0
DXF ScaleX= 0
DXF ScaleY= 0

--- SLSBRYRN.p01 (plan) ---

Plan Title=Floodplain
Program Version=6.10
Short Identifier=Floodplain
Geom File=g01
Flow File=f01
Subcritical Flow
K Sum by GR= 0
Std Step Tol= 0.01
Critical Tol= 0.01
Num of Std Step Trials= 20
Max Error Tol= 0.3
Flow Tol Ratio= 0.001
Split Flow NTrial= 30
Split Flow Tol= 0.02
Split Flow Ratio= 0.02
Log Output Level= 0
Friction Slope Method= 1
Unsteady Friction Slope Method= 2
Unsteady Bridges Friction Slope Method= 1
Parabolic Critical Depth
Global Vel Dist= 0 , 0 , 0
Global Log Level= 0
CheckData=True
Encroach Param=-1 ,0,0, 0
Mapping Interval=1HOUR
Computation Time Step Use Courant=        0
Computation Time Step Use Time Series=    0
Computation Time Step Count To Double=0
Computation Time Step Max Doubling=0
Computation Time Step Max Halving=0
Computation Time Step Residence Courant=0
Run HTab= 0
Run UNet= 0
Run Sediment= 0
Run PostProcess= 0
Run WQNet= 0
Run RASMapper=-1
UNET Theta= 0
UNET Theta Warmup= 0
UNET ZTol= 0
UNET ZSATol= 0
UNET MxIter= 0
UNET Max Iter WO Improvement= 0
UNET MaxInSteps= 0
UNET DtIC= 0
UNET DtMin= 0
UNET MaxCRTS= 0
UNET WFStab= 0
UNET SFStab= 0
UNET WFX= 1
UNET SFX= 1
UNET Gravity=32.174
UNET 1D Methodology=Finite Difference
UNET DSS MLevel= 1
UNET Pardiso=0
UNET DZMax Abort= 0
UNET Use Existing IB Tables= 0
UNET Froude Reduction=False
UNET Froude Limit= 0
UNET Froude Power= 0
UNET D1 Cores= 0
UNET WindReference=Eulerian
UNET WindDragFormulation=Hsu (1988)
UNET D2 Coriolis=0
UNET D2 Cores= 0
UNET D2 Theta= 1
UNET D2 Theta Warmup= 1
UNET D2 Z Tol= 0.01
UNET D2 Volume Tol= 0.01
UNET D2 Max Iterations= 20
UNET D2 Equation= 0
UNET D2 RampUpFraction=0.1
UNET D2 TimeSlices= 1
UNET D2 Turbulence Formulation=Non-Conservative (original)
UNET D2 Eddy Viscosity=0.3
UNET D2 Transverse Eddy Viscosity=0.1
UNET D2 Smagorinsky Mixing=0
UNET D2 BCVolumeCheck=0
UNET D2 Cores=0
UNET D2 SolverType=PARDISO (Direct)
UNET D2 Minimum Iterations= 2147483647
UNET D2 Maximum Iterations= 2147483647
UNET D2 Restart Number= 10
UNET D2 Relaxation Coeff=1.3
UNET D2 SOR Precondition Iterations= 10
UNET D2 ILUT Maximum Fill= 8
UNET D2 ILUT Tolerance=1E-08
UNET D1D2 MaxIter= 0
UNET D1D2 ZTol=0.01
UNET D1D2 QTol=0.1
UNET D1D2 MinQTol=1
Write IC File= 0
Write IC File at Fixed DateTime=0
Write IC File at Sim End=0
Echo Input=False
Echo Parameters=False
Echo Output=False
Write Detailed= 0
HDF Write Warmup=0
HDF Write Time Slices=0
HDF Flush=0
HDF Compression= 1
HDF Chunk Size= 1
HDF Spatial Parts= 1
HDF Use Max Rows=0
HDF Fixed Rows= 1
Calibration Method= 0
Calibration Iterations= 20
Calibration Max Change=0.05
Calibration Tolerance=0.2
Calibration Maximum=1.5
Calibration Minimum=0.5
Calibration Optimization Method= 1
WQ AD Non Conservative
WQ ULTIMATE=-1
WQ Max Comp Step=1HOUR
WQ Output Interval=15MIN
WQ Output Selected Increments= 0
WQ Output face flow=0
WQ Output face velocity=0
WQ Output face area=0
WQ Output face dispersion=0
WQ Output cell volume=0
WQ Output cell surface area=0
WQ Output cell continuity=0
WQ Output cumulative cell continuity=0
WQ Output face conc=0
WQ Output face dconc_dx=0
WQ Output face courant=0
WQ Output face peclet=0
WQ Output face adv mass=0
WQ Output face disp mass=0
WQ Output cell mass=0
WQ Output cell source sink temp=0
WQ Output nsm pathways=0
WQ Output nsm derived pathways=0
WQ Create Restart=0
WQ Fixed Restart=0
WQ System Summary=0
WQ Write To DSS=0
Sorting and Armoring Iterations= 10
XS Update Threshold= 0.02
Bed Roughness Predictor= 0
Hydraulics Update Threshold= 0.02
Energy Slope Method= 1
Volume Change Method= 1
Sediment Retention Method= 0
Sediment TS Multiplier= 1
Warm Up Method= 0
XS Weighting Method= 0
Number of US Weighted Cross Sections= 1
Number of DS Weighted Cross Sections= 1
Upstream XS Weight=0
Main XS Weight=1
Downstream XS Weight=0
Number of DS XS's Weighted with US Boundary= 1
Upstream Boundary Weight= 1
Weight of XSs Associated with US Boundary= 0
Number of US XS's Weighted with DS Boundary= 1
Downstream Boundary Weight= 0.5
Weight of XSs Associated with DS Boundary= 0.5
Percentile Method= 0
Sediment Output Level= 3
Mass or Volume Output= 0
Output Increment Type= 1
Profile and TS Output Increment= 1
Transport Output Increment 1
XS Output Flag= 0
XS Output Increment= 10
Read HDF5 Sediment Hotstart= 0
Sediment Hotstart Type= 0
Write Gradation File= 0
Read Gradation Hotstart= 0
Write HDF5 File= 1
Write Binary Output= 1
Write DSS Sediment File= 0
DSS Sediment Output Type= 1
SV Curve= 0
Specific Gage Flag= 0
Subcell Erosion Methods= 0
Subcell Deposition Methods= 0
Advection Scheme= 1
Matrix Solver= 0
Implicit Weighting Factor= 1
Maximum Outer Loop Convergence Iterations= 5
Convergence Maximum Absolute= 0.001
Convergence RMSE= 0.0001
Grain Fractions Max Abs Error= 0.001
Max Subgrid Regions= 1
Max Subgrid Length Scale= 3.402823E+38
Initial Layer Thickness= 3.402823E+38
Min Layer Thickness= 3.402823E+38
Max Layer Thickness= 3.402823E+38
Number of Layers= 5

--- SLSBRYRN.f01 (steady flow) ---

Flow Title=Flow
Program Version=6.10
Number of Profiles= 6
Profile Names=01pct,10pct,04pct,02pct,0_2pct,01plus
River Rch & RM=SLSBRYRN,Main,16843
     734     392     518     623    1020    1090
River Rch & RM=SLSBRYRN,Main,12289
     816     437     577     693    1130    1210
River Rch & RM=SLSBRYRN,Main,8998
     924     497     656     786    1280    1370
River Rch & RM=SLSBRYRN,Main,4772
    1070     577     758     907    1470    1580
Boundary for River Rch & Prof#=SLSBRYRN,Main            , 1
Up Type= 0
Dn Type= 3
Dn Slope=0.012955
Boundary for River Rch & Prof#=SLSBRYRN,Main            , 2
Up Type= 0
Dn Type= 3
Dn Slope=0.012955
Boundary for River Rch & Prof#=SLSBRYRN,Main            , 3
Up Type= 0
Dn Type= 3
Dn Slope=0.012955
Boundary for River Rch & Prof#=SLSBRYRN,Main            , 4
Up Type= 0
Dn Type= 3
Dn Slope=0.012955
Boundary for River Rch & Prof#=SLSBRYRN,Main            , 5
Up Type= 0
Dn Type= 3
Dn Slope=0.012955
Boundary for River Rch & Prof#=SLSBRYRN,Main            , 6
Up Type= 0
Dn Type= 3
Dn Slope=0.012955
DSS Import GetInterval= 0
DSS Import GetPeak= 0
DSS Import FillOption= 0

--- SLSBRYRN.g01 (geometry) ---

Geom Title=Geometry
Program Version=6.10

River Reach=SLSBRYRN        ,Main
Reach XY= 30
2324141.50124428543705.0293016352323589.24758077543723.898649935
2323030.86900194543425.791795806     2321100.654      543976.448
     2320358.923      543936.4812319935.00881646543773.078322338
     2319692.041      543800.978     2319225.724      543493.149
2318934.42413034543543.803166113     2318404.338       543214.05
     2317724.148      542305.1892317607.02107811541704.476087063
2317444.14318489541399.364890356     2317198.744      541403.913
     2316710.273      540836.624     2316639.774      540539.788
     2316037.396      540453.618     2315550.177      540535.472
      2314487.51      539880.5182313851.41097996539671.938964927
     2313102.655      539671.291     2313010.626      539806.952
       2312844.3      539796.487     2312593.961      539466.581
     2312465.122      539634.373     2311869.367      539235.864
      2311673.25      539247.081     2311544.853      539405.622
2310796.35146379539395.168343085     2310568.101      539525.836

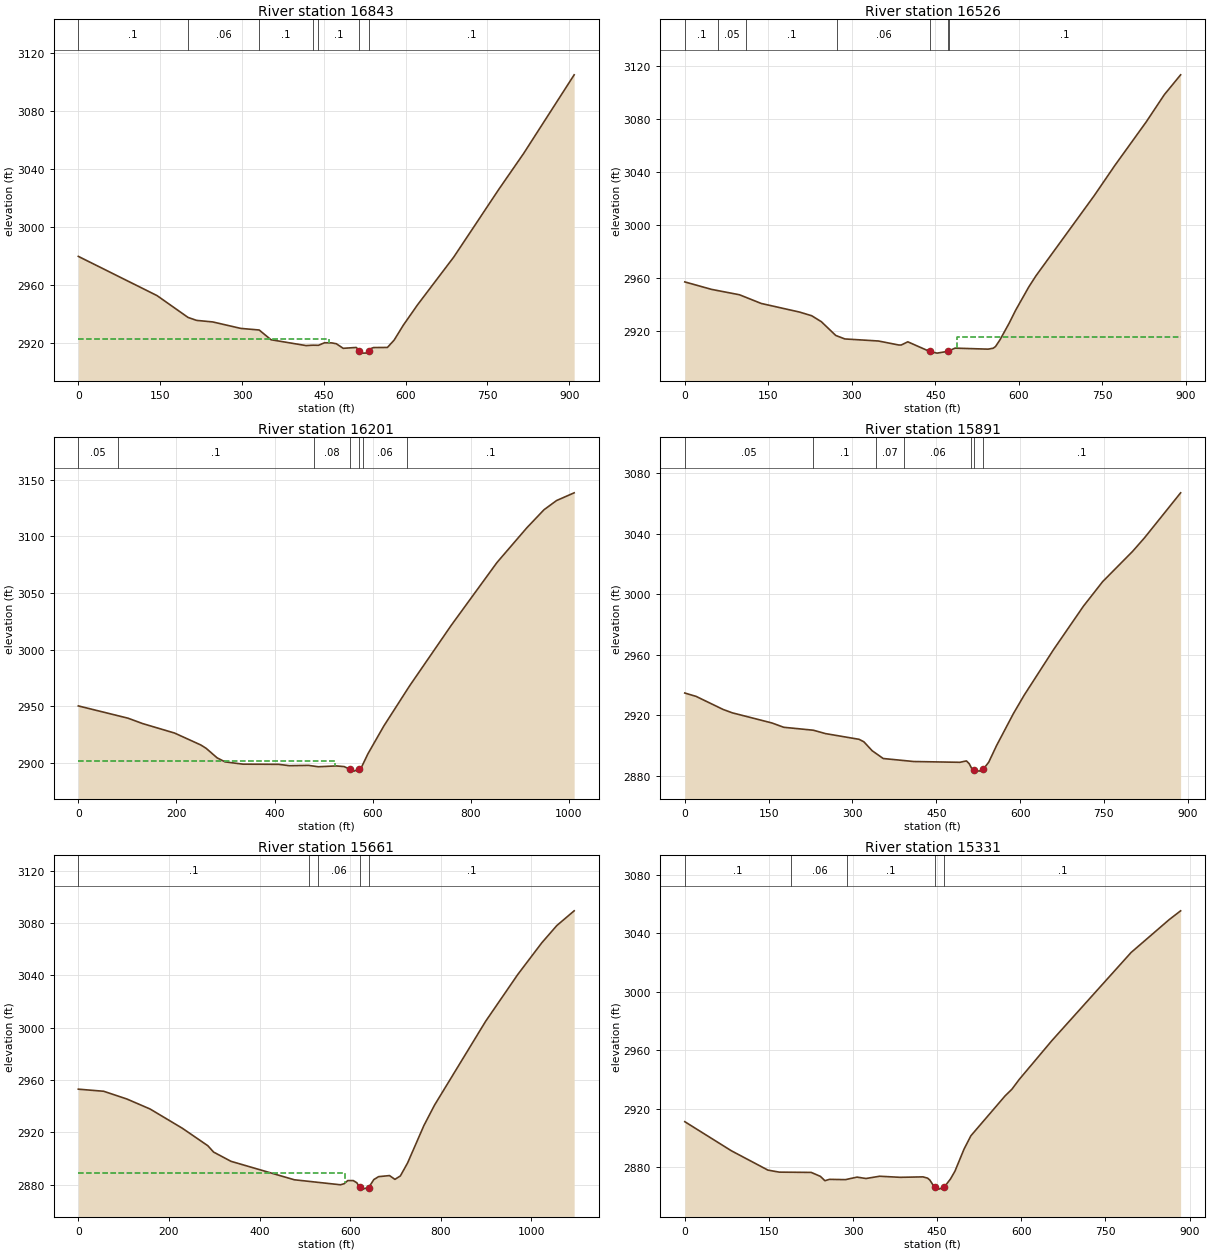
Type RM Length L Ch R = 1 ,16843   ,316.7,316.7,316.7
XS GIS Cut Line= 4
2324409.66384185543279.6489869832324232.04690615543425.410711384
2324110.41791758543752.6506092132324176.05895903544076.029269308
#Sta/Elev= 30
       0 2979.79   144.3 2952.69   201.1 2937.62   216.8 2935.58   246.6 2934.49
   297.9 2930.03   331.5 2928.93   353.3 2922.19   417.3 2918.18   430.1 2918.44
   440.1 2918.36   451.4 2920.12   464.2 2920.04   472.8 2919.46   485.6 2916.28
   509.5 2916.88   515.4 2914.53   521.9 2912.96   528.2 2913.03  533.642914.551
   536.8 2916.19     541  2916.8   566.6 2916.89   578.9 2921.96   595.7 2932.24
   621.5 2946.17   688.3 2979.38   770.8  3026.1   816.2 3050.82   908.9 3105.19
#Mann= 7 ,-1,0
       0      .1       0   201.1     .06       0   331.5      .1       0
   430.1     .06       0   440.1      .1       0   515.4    .045       0
  533.64      .1       0
#XS Ineff= 2 , 0
          459.63 2922.64
Permanent Ineff=
       F       F
Bank Sta=515.4,533.64
XS Rating Curve= 0 ,0
Exp/Cntr(USF)=0,0
Exp/Cntr=0.3,0.1

Type RM Length L Ch R = 1 ,16526   ,322,325.7,331.3
XS GIS Cut Line= 4
2323907.94606934543266.3072289862323804.22875524543519.580412509
2323846.60173447543826.7845119362323891.11919519 544130.14182457
#Sta/Elev= 30
       0 2956.88      48 2951.23    98.2 2947.15   137.4 2940.56   206.3 2934.04
   227.9 2931.28   245.2 2926.78   271.1 2916.36   287.4 2913.73     348 2912.15
   384.3 2909.13   388.6 2909.13   400.5 2911.54   439.6 2904.29     453 2902.99
   472.3 2904.32   485.3 2906.77   544.7    2906   553.9 2906.71     558    2908
     566 2913.06   582.2 2925.43   594.2 2935.51   617.9 2953.19   630.7 2961.55
   735.4 3022.26   772.2 3044.96   828.8 3078.08   861.1 3098.55   890.4 3113.59
#Mann= 7 ,-1,0
       0      .1       0      60     .05       0     110      .1       0
  273.69     .06       0   439.6    .045       0   472.3     .06       0
  473.69      .1       0
#XS Ineff= 2 , 0
                          489.45         2915.52
Permanent Ineff=
       F       F
Bank Sta=439.6,472.3
XS Rating Curve= 0 ,0
Exp/Cntr(USF)=0,0
Exp/Cntr=0.3,0.1

Type RM Length L Ch R = 1 ,16201   ,303.5,309.6,316.7
XS GIS Cut Line= 3
2323789.76013606543285.4573369692323559.25996906543407.027186426
2323445.70217715544148.815673675
#Sta/Elev= 30
       0 2950.21   101.3 2939.37   131.2  2934.6   196.4 2926.22   249.7 2915.73
   260.6 2912.77     283 2904.34   299.2 2900.79   335.6 2898.77   408.4 2898.63
   430.1 2897.42   469.1  2897.7   489.4 2896.49   525.8 2897.22     542 2896.63
   554.1 2894.24   558.2 2892.86   562.2 2892.62   571.7 2894.33   574.4 2894.86
   578.4 2896.99   590.5 2907.92   623.1 2932.61   675.5 2967.94   760.5 3021.45
   853.6 3076.83   914.4 3107.45   949.5 3123.44     975 3131.55    1011 3138.39
#Mann= 7 ,-1,0
       0     .05       0      80      .1       0  480.59     .08       0
   554.1    .045       0   571.7     .08       0  580.59     .06       0
  670.59      .1       0
#XS Ineff= 2 , 0
          524.05 2901.59
Permanent Ineff=
       F       F
Bank Sta=554.1,571.7
XS Rating Curve= 0 ,0
Exp/Cntr(USF)=0,0
Exp/Cntr=0.3,0.1

Type RM Length L Ch R = 1 ,15891   ,237.8,230.4,219.9
XS GIS Cut Line= 4
2323678.71488023543258.8245867262323406.98207495543334.198628373
2323246.75924723543552.6843025342323121.11798406543862.414072698
#Sta/Elev= 30
       0 2934.64    20.2 2932.42    68.7 2923.76    85.2 2921.53   156.2 2914.82
     177    2912     230 2910.06   251.7 2907.83   311.9 2904.04   320.5 2902.38
   335.3 2896.49   355.1 2891.35   409.7 2889.37   492.2 2888.85   503.9 2889.77
   508.9 2887.94   513.9 2884.42   516.7 2883.95   526.5 2883.02   533.7 2884.12
   543.8 2888.91   557.8 2899.87     588 2921.05   607.2 2933.18   659.7 2963.26
   713.2 2991.99   747.7 3008.27     801 3028.17   822.5 3037.19   887.2 3066.96
#Mann= 7 ,-1,0
       0     .05       0     230      .1       0  341.99     .07       0
  391.99     .06       0  511.99      .1       0   516.7    .045       0
   533.7      .1       0
Bank Sta=516.7,533.7
XS Rating Curve= 0 ,0
Exp/Cntr(USF)=0,0
Exp/Cntr=0.3,0.1

Type RM Length L Ch R = 1 ,15661   ,331.7,329.3,323.7
XS GIS Cut Line= 3
2323487.65776372543005.9103589042323062.63670455543347.923673617
2323037.30692436543896.447472602
#Sta/Elev= 30
       0 2953.04      56 2951.44   107.2 2945.52   158.5 2937.87   229.6 2923.18
   285.9 2909.83   298.7 2904.95     337 2897.91   476.8  2883.8   578.8 2879.97
   586.8 2880.78   594.8 2883.17   606.9  2883.2   614.9 2881.51  621.07 2878.04
   626.9 2876.65     641 2877.87   652.4 2883.94   662.9 2886.19     687    2887
     699 2884.12     711 2886.74     727  2896.7     763 2925.27   786.4 2940.84
   899.2 3004.89   970.1 3040.64  1023.3 3064.92  1056.4 3078.09  1094.7 3089.34
#Mann= 5 ,-1,0
       0      .1       0     510     .08       0     530     .06       0
  621.07    .045       0     641      .1       0
#XS Ineff= 2 , 0
          589.52  2889.3
Permanent Ineff=
       F       F
Bank Sta=621.07,641
XS Rating Curve= 0 ,0
Exp/Cntr(USF)=0,0
Exp/Cntr=0.3,0.1

Type RM Length L Ch R = 1 ,15331   ,386.9,383.3,379.2
XS GIS Cut Line= 2
2322664.93411831543039.3683175652322822.84909615543909.158854318
#Sta/Elev= 30
       0 2911.16    83.1 2891.24   148.2 2878.02   168.5 2876.63   225.4 2876.44
   241.8 2873.73   249.8 2870.76     258 2871.69   286.4  2871.5   307.1 2873.22
     323 2872.27   347.4 2873.82     384 2873.08   424.6 2873.39   432.8 2872.53
   436.8 2871.25   445.3 2866.21   453.1    2865  462.462866.367   473.4  2871.8
   481.6 2877.23   497.8 2892.35   510.1 2901.54     571  2928.8   583.2 2933.38
   596.1 2940.01   654.6 2966.72   795.7 3026.98   863.7 3049.51     884  3055.5
#Mann= 5 ,-1,0
       0      .1       0     190     .06       0     290      .1       0
   445.3    .045       0  462.46      .1       0
Bank Sta=445.3,462.46
XS Rating Curve= 0 ,0
Exp/Cntr(USF)=0,0
Exp/Cntr=0.3,0.1

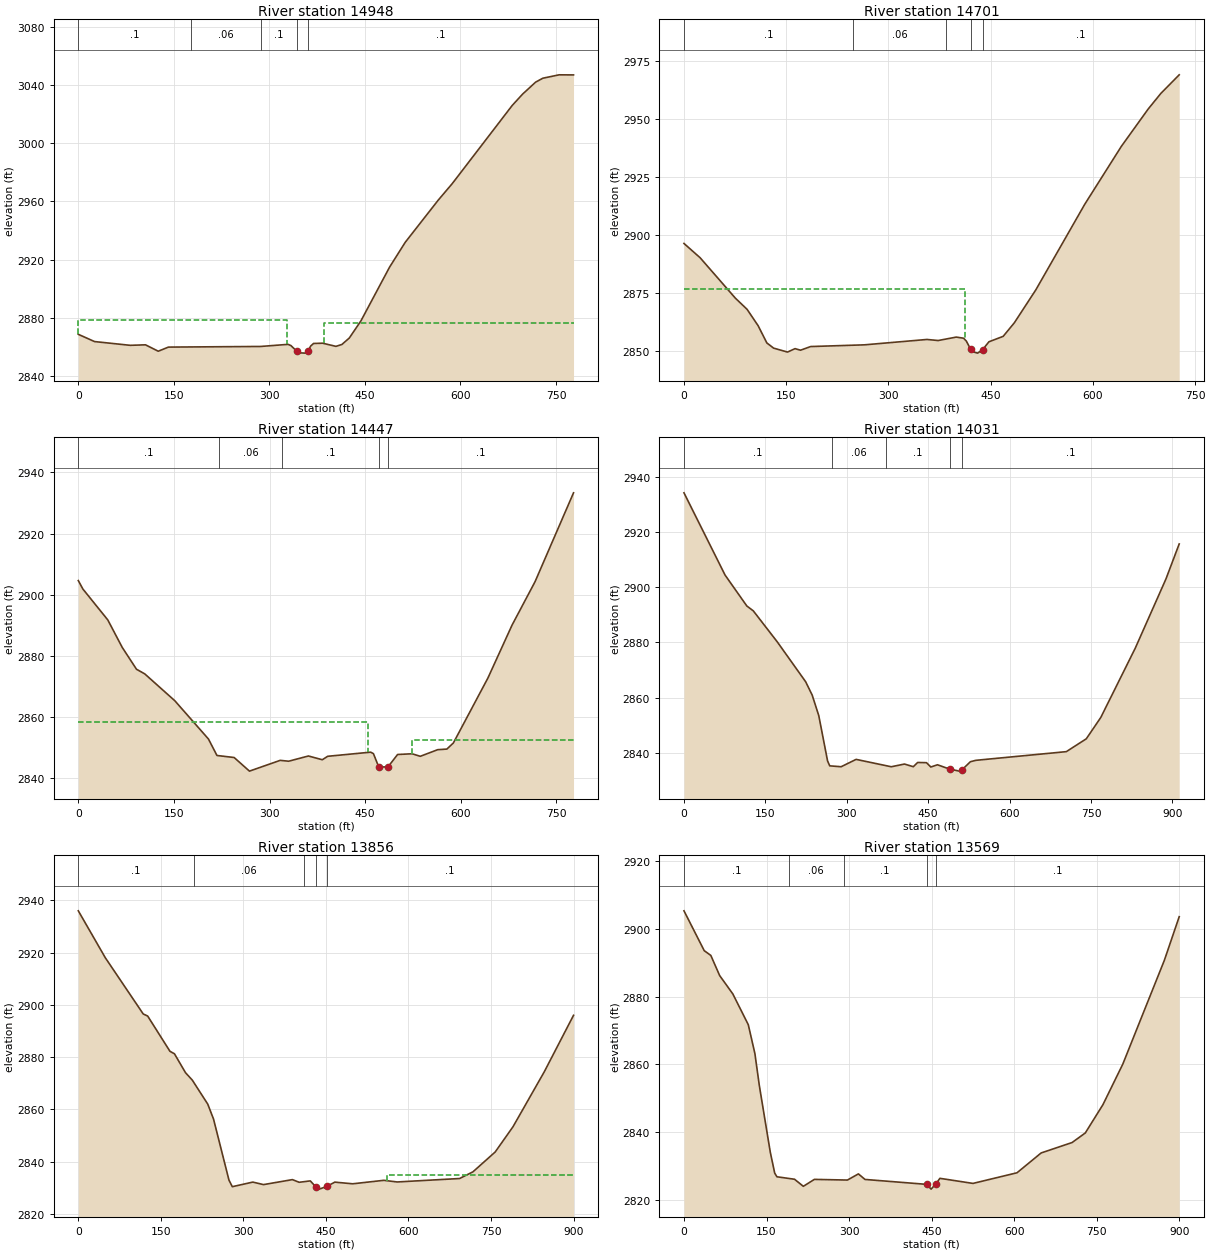
Type RM Length L Ch R = 1 ,14948   ,243.7,247.3,249.4
XS GIS Cut Line= 5
2322305.35881478543247.6575435612322303.08472858543394.039329301
2322365.76367645543561.5558816112322410.81400894543653.673475266
2322485.54999537543995.341411475
#Sta/Elev= 30
       0 2868.76    25.5 2863.77    81.5 2861.19   105.5 2861.53   125.5 2857.14
   141.5 2859.97   286.4 2860.41   329.3 2861.85   333.7 2861.06342.68992857.302
   347.1 2856.05     356 2855.83360.48992857.167   364.9 2860.75   369.4 2862.47
   383.6 2862.64   404.5 2860.48   413.9 2861.79   425.5 2866.22   443.7 2877.97
   488.7  2914.9   513.3 2931.96   565.2 2960.98     587 2972.21   681.2 3025.93
   697.5 3033.72     718 3041.97   729.3 3044.66   754.9 3046.99   777.5 3046.93
#Mann= 5 ,-1,0
       0      .1       0   176.4     .06       0   286.4      .1       0
342.6899    .045       0360.4899      .1       0
#XS Ineff= 2 , 0
          328.11  2878.6  385.35         2876.64
Permanent Ineff=
       F       F
Bank Sta=342.6899,360.4899
XS Rating Curve= 0 ,0
Exp/Cntr(USF)=0,0
Exp/Cntr=0.3,0.1

Type RM Length L Ch R = 1 ,14701   ,254.7,253.6,252.7
XS GIS Cut Line= 4
2322003.80738581543277.9751933472322024.62989361 543394.74550196
 2322127.6218393543536.8439601232322237.75267929543955.227605231
#Sta/Elev= 30
       0 2896.36    23.6 2890.22    75.5 2872.71    92.6 2867.92   108.9  2860.8
   121.6  2853.4   131.5 2851.16   151.9 2849.46     163 2850.94     171 2850.26
   185.9 2851.84   264.9 2852.58   356.5  2854.9     373 2854.44   399.6 2855.93
   410.3 2855.44   414.4 2854.17420.74762850.613   422.9 2849.65     431    2849
438.14942850.495   447.5  2853.9   468.4 2856.25   484.7 2862.07   516.3 2876.32
   588.1 2913.29   641.9 2938.34   681.2 2954.43   699.8 2961.17   726.7 2969.19
#Mann= 5 ,-1,0
       0      .1       0  248.61     .06       0  384.11      .1       0
420.7476    .045       0438.1494      .1       0
#XS Ineff= 2 , 0
          411.96 2876.54
Permanent Ineff=
       F       F
Bank Sta=420.7476,438.1494
XS Rating Curve= 0 ,0
Exp/Cntr(USF)=0,0
Exp/Cntr=0.3,0.1

Type RM Length L Ch R = 1 ,14447   ,412.4,415.6,416.5
XS GIS Cut Line= 4
2321736.75258921543326.9521669462321897.87819422543667.160733594
 2321940.2877443543793.5045092162322157.22506928543949.546198917
#Sta/Elev= 30
       0 2904.64     7.2 2901.88    46.3 2891.77    68.9  2882.8    91.3 2875.65
   104.3 2874.12   151.4 2865.35   204.2 2852.83   217.5 2847.45   244.5 2846.78
   268.5 2842.33   316.7 2845.85     330 2845.57     361 2847.28   382.8 2846.05
   391.2 2847.18   458.7 2848.53     463 2848.04   471.3 2843.71485.77382843.691
   500.9 2847.77   523.7    2848   536.5 2847.18   563.8 2849.34   578.2 2849.54
   588.4 2851.54   642.6 2872.78   680.4 2890.05   716.5 2904.26   776.9 2933.34
#Mann= 5 ,-1,0
       0      .1       0     220     .06       0     320      .1       0
   471.3    .045       0485.7738      .1       0
#XS Ineff= 2 , 0
          454.49 2858.54  523.34         2852.36
Permanent Ineff=
       F       F
Bank Sta=471.3,485.7738
XS Rating Curve= 0 ,0
Exp/Cntr(USF)=0,0
Exp/Cntr=0.3,0.1

Type RM Length L Ch R = 1 ,14031   ,175.3,175.3,175.5
XS GIS Cut Line= 4
2321479.65810385543345.7500082452321498.46296846 543577.29757443
2321547.84416418543889.3472313952321666.78540265 544233.78701462
#Sta/Elev= 30
       0  2934.1    75.7 2904.35   115.8 2893.16   127.8 2891.38     172 2880.15
   224.2 2865.75   236.2 2860.94   248.4 2853.48   264.6  2837.1   268.6 2835.31
   289.6 2834.99   317.2 2837.65     382 2834.98   406.3 2835.96   422.6    2835
   430.6 2836.53   446.8 2836.46   454.9 2834.89   467.1  2835.7   489.9 2834.11
   507.6  2833.4512.82752833.979   527.8  2836.8   537.9 2837.31   704.6 2840.45
   741.4  2845.1   768.1 2852.82   831.5 2877.84   888.1  2902.9   912.6 2915.61
#Mann= 5 ,-1,0
       0      .1       0  272.31     .06       0  372.31      .1       0
   489.9    .045       0512.8275      .1       0
Bank Sta=489.9,512.8275
XS Rating Curve= 0 ,0
Exp/Cntr(USF)=0,0
Exp/Cntr=0.3,0.1

Type RM Length L Ch R = 1 ,13856   ,285.1,286.7,286.8
XS GIS Cut Line= 2
2321300.01466669543408.5934921492321438.84220002544297.821762048
#Sta/Elev= 30
       0 2936.01    49.2 2918.01     118 2896.53   126.1 2895.73   166.6 2882.23
   174.7  2881.3   194.9 2874.03   207.1 2871.23   235.3 2862.01   245.8 2856.27
   273.8 2832.94   279.9 2830.41   317.1 2832.17   336.6 2831.21   389.1 2833.12
   401.4  2832.1   421.6 2832.63   431.4 2830.41   437.8 2829.48   451.5  2830.5
   466.2 2832.16   498.6 2831.52   555.2 2832.85   579.5 2832.22   692.9 2833.54
   717.2  2836.1   757.7 2843.71     790 2853.36   846.7 2874.34     900 2896.01
#Mann= 5 ,-1,0
       0      .1       0     210     .06       0     410      .1       0
   431.4    .045       0   451.5      .1       0
#XS Ineff= 2 , 0
                          560.94         2834.95
Permanent Ineff=
       F       F
Bank Sta=431.4,451.5
XS Rating Curve= 0 ,0
Exp/Cntr(USF)=0,0
Exp/Cntr=0.3,0.1

Type RM Length L Ch R = 1 ,13569   ,266.9,268.6,269.4
XS GIS Cut Line= 2
2321098.84598912543524.3986421382321133.73305207544423.722217298
#Sta/Elev= 30
       0 2905.33    36.8 2893.56    48.8 2892.15    64.8 2886.21    88.8 2880.77
   116.9 2871.67   128.9 2863.14   136.9 2853.73   156.9 2833.96   164.9 2827.82
   168.9 2826.74   200.9 2826.01   216.9 2823.92     237 2825.97     297 2825.77
     317 2827.59     329 2825.95   441.1  2824.5   449.1 2823.09   457.5 2824.57
   465.1 2826.28   525.2 2824.78   605.2 2827.92   649.1 2833.78   705.3 2836.86
   729.3 2839.68   761.4 2848.05   797.4    2860   872.9 2890.66     900 2903.59
#Mann= 5 ,-1,0
       0      .1       0     190     .06       0     290      .1       0
   441.1    .045       0   457.5      .1       0
Bank Sta=441.1,457.5
XS Rating Curve= 0 ,0
Exp/Cntr(USF)=0,0
Exp/Cntr=0.3,0.1

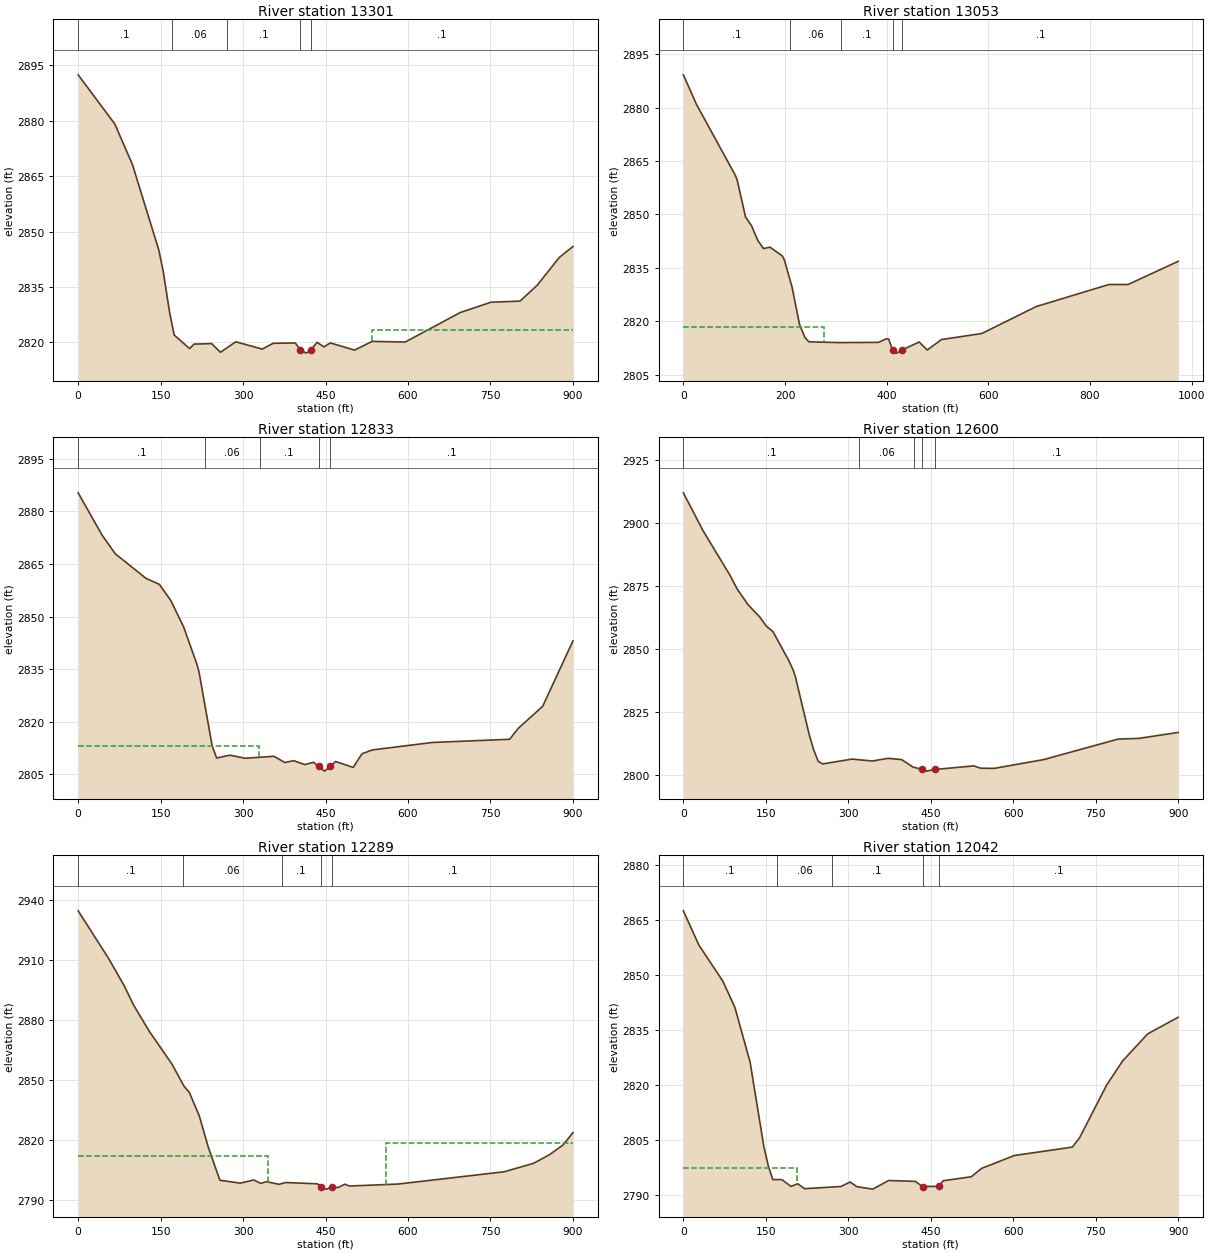
Type RM Length L Ch R = 1 ,13301   ,248,247.6,245
XS GIS Cut Line= 2
2320870.19636886543550.5339291362320841.78668707544450.085422927
#Sta/Elev= 30
       0 2892.36    66.7 2879.06    98.7 2868.13   146.7 2844.99   154.7 2839.21
   166.7 2827.82   174.7 2822.01   202.7 2818.35   210.8 2819.56   242.8 2819.69
   258.8 2817.35   286.8 2820.19   334.8 2818.21   354.8 2819.78   394.8 2819.86
   404.1 2818.08   414.9 2817.12   423.5 2818.03   434.6 2820.03   446.9 2818.82
   458.9 2819.87   502.9 2817.94   534.9 2820.29   594.9 2820.12     695 2828.09
     751 2830.89   803.7 2831.18   835.1 2835.49   875.1 2842.98     900 2845.96
#Mann= 5 ,-1,0
       0      .1       0     170     .06       0     270      .1       0
   404.1    .045       0   423.5      .1       0
#XS Ineff= 2 , 0
                          535.21         2823.25
Permanent Ineff=
       F       F
Bank Sta=404.1,423.5
XS Rating Curve= 0 ,0
Exp/Cntr(USF)=0,0
Exp/Cntr=0.3,0.1

Type RM Length L Ch R = 1 ,13053   ,218.9,220.5,221.6
XS GIS Cut Line= 5
2320673.65316105543507.5597648282320631.94225962 543902.02571836
2320635.51747975 544036.692342982320803.55282551544295.299931852
2320810.70326576544428.774816431
#Sta/Elev= 30
       0 2889.23    25.8 2880.92   102.2 2860.99   106.2 2859.48   122.3 2849.27
   134.4 2846.75   146.4  2842.7   157.6  2840.4   170.6 2840.78   194.7 2838.32
   198.7  2837.2   213.8 2829.61   228.4 2819.17   238.9 2815.46     247 2814.19
   307.3 2813.97   383.7 2814.03   399.8 2815.06   403.9 2814.95   411.7 2811.87
   419.8 2811.01   431.1 2811.94   463.8 2814.14   479.8 2811.89   507.9 2814.83
   587.1 2816.52   694.2  2824.1   837.3  2830.3     875  2830.3   973.5 2836.81
#Mann= 5 ,-1,0
       0      .1       0     210     .06       0     310      .1       0
   411.7    .045       0   431.1      .1       0
#XS Ineff= 2 , 0
          275.77 2818.25
Permanent Ineff=
       F       F
Bank Sta=411.7,431.1
XS Rating Curve= 0 ,0
Exp/Cntr(USF)=0,0
Exp/Cntr=0.3,0.1

Type RM Length L Ch R = 1 ,12833   ,230.6,232.7,235.3
XS GIS Cut Line= 2
2320438.90019007543485.7556922672320386.07930401544384.204329639
#Sta/Elev= 30
       0 2885.28    43.5 2873.23    67.5  2867.9   123.6 2860.88   147.7 2859.19
   168.5 2854.58   191.8 2847.08   215.8 2836.51   219.8 2834.26   243.8 2813.07
   251.9 2809.68   275.9 2810.49   303.9 2809.61     356 2810.17   376.1 2808.38
   392.1 2808.93   412.1  2807.8   428.2 2808.46   437.52807.266   448.2 2805.94
   458.62807.263   468.2 2808.68   500.3 2807.01   516.3  2810.9   535.6    2812
   644.5 2814.11   784.8 2815.02   800.8 2818.18   844.9 2824.42     900 2843.05
#Mann= 5 ,-1,0
       0      .1       0     230     .06       0     330      .1       0
   437.5    .045       0   458.6      .1       0
#XS Ineff= 2 , 0
          328.17 2813.05
Permanent Ineff=
       F       F
Bank Sta=437.5,458.6
XS Rating Curve= 0 ,0
Exp/Cntr(USF)=0,0
Exp/Cntr=0.3,0.1

Type RM Length L Ch R = 1 ,12600   ,309.9,311.4,311.9
XS GIS Cut Line= 2
2320305.34009054543410.2876197182320103.49522197544287.361532813
#Sta/Elev= 30
       0  2911.8    35.8  2896.8    85.1 2879.05    97.4 2873.88   117.9 2867.41
   138.4 2862.77   150.7 2859.05     163 2856.81   191.8 2845.36     200 2841.44
   204.1 2838.65   228.7  2816.2   236.9 2810.06   245.1 2805.48   253.3 2804.41
     307 2806.33   343.7 2805.57   372.4 2806.63     397 2806.12   417.5  2803.2
   433.9 2802.25   442.2 2801.56   457.2 2802.21   528.4 2803.64   540.6 2802.72
   565.3 2802.64   655.6 2806.14     791 2814.27     828 2814.51     900 2816.89
#Mann= 5 ,-1,0
       0      .1       0     320     .06       0     420      .1       0
   433.9    .045       0   457.2      .1       0
Bank Sta=433.9,457.2
XS Rating Curve= 0 ,0
Exp/Cntr(USF)=0,0
Exp/Cntr=0.3,0.1

Type RM Length L Ch R = 1 ,12289   ,247.3,246.2,249.5
XS GIS Cut Line= 2
2320022.24549036543336.1535623522319792.38410411544206.305125652
#Sta/Elev= 30
       0 2934.78    54.8 2911.16    83.8 2897.22   100.7  2887.6   129.3 2874.43
   170.7 2857.94   192.3 2847.01   202.2 2843.77   220.3 2832.04   236.9 2816.16
   257.8 2799.75   294.8 2798.29   319.6 2799.88     332 2798.15   342.9 2799.03
   365.1  2797.7   377.5  2798.6   435.5 2797.95   441.1 2796.28     452 2795.29
   462.3 2796.35   472.7  2796.1   485.1 2797.75   493.4 2796.85   581.8 2797.83
   774.9 2803.99   828.5 2808.24   857.5 2812.58   882.3 2817.49     900 2823.59
#Mann= 5 ,-1,0
       0      .1       0     190     .06       0     370      .1       0
   441.1    .045       0   462.3      .1       0
#XS Ineff= 2 , 0
          345.51    2812   559.8         2818.63
Permanent Ineff=
       F       F
Bank Sta=441.1,462.3
XS Rating Curve= 0 ,0
Exp/Cntr(USF)=0,0
Exp/Cntr=0.3,0.1

Type RM Length L Ch R = 1 ,12042   ,212.1,210.6,215.2
XS GIS Cut Line= 2
2319776.84528667543359.6920756992319551.17736073544230.940597765
#Sta/Elev= 30
       0 2867.38      28  2858.1    71.8  2848.2    93.7 2841.06   121.4 2826.11
   146.2 2803.26   154.4 2797.88   162.7 2794.11   179.2 2794.09   195.7 2792.24
   208.1 2792.95   220.5 2791.62   286.6 2792.22   303.2 2793.44   315.6 2792.17
   344.5  2791.5   373.4 2793.85   421.9 2793.61     435  2792.2   464.3 2792.27
   472.6 2793.79   523.6 2794.87   542.8 2797.18   602.4 2800.68   707.4 2802.95
   720.5 2805.46   770.1 2819.92     799 2826.45   844.5 2833.82     900 2838.37
#Mann= 5 ,-1,0
       0      .1       0     170     .06       0     270      .1       0
     435    .045       0   464.3      .1       0
#XS Ineff= 2 , 0
           206.2 2797.25
Permanent Ineff=
       F       F
Bank Sta=435,464.3
XS Rating Curve= 0 ,0
Exp/Cntr(USF)=0,0
Exp/Cntr=0.3,0.1

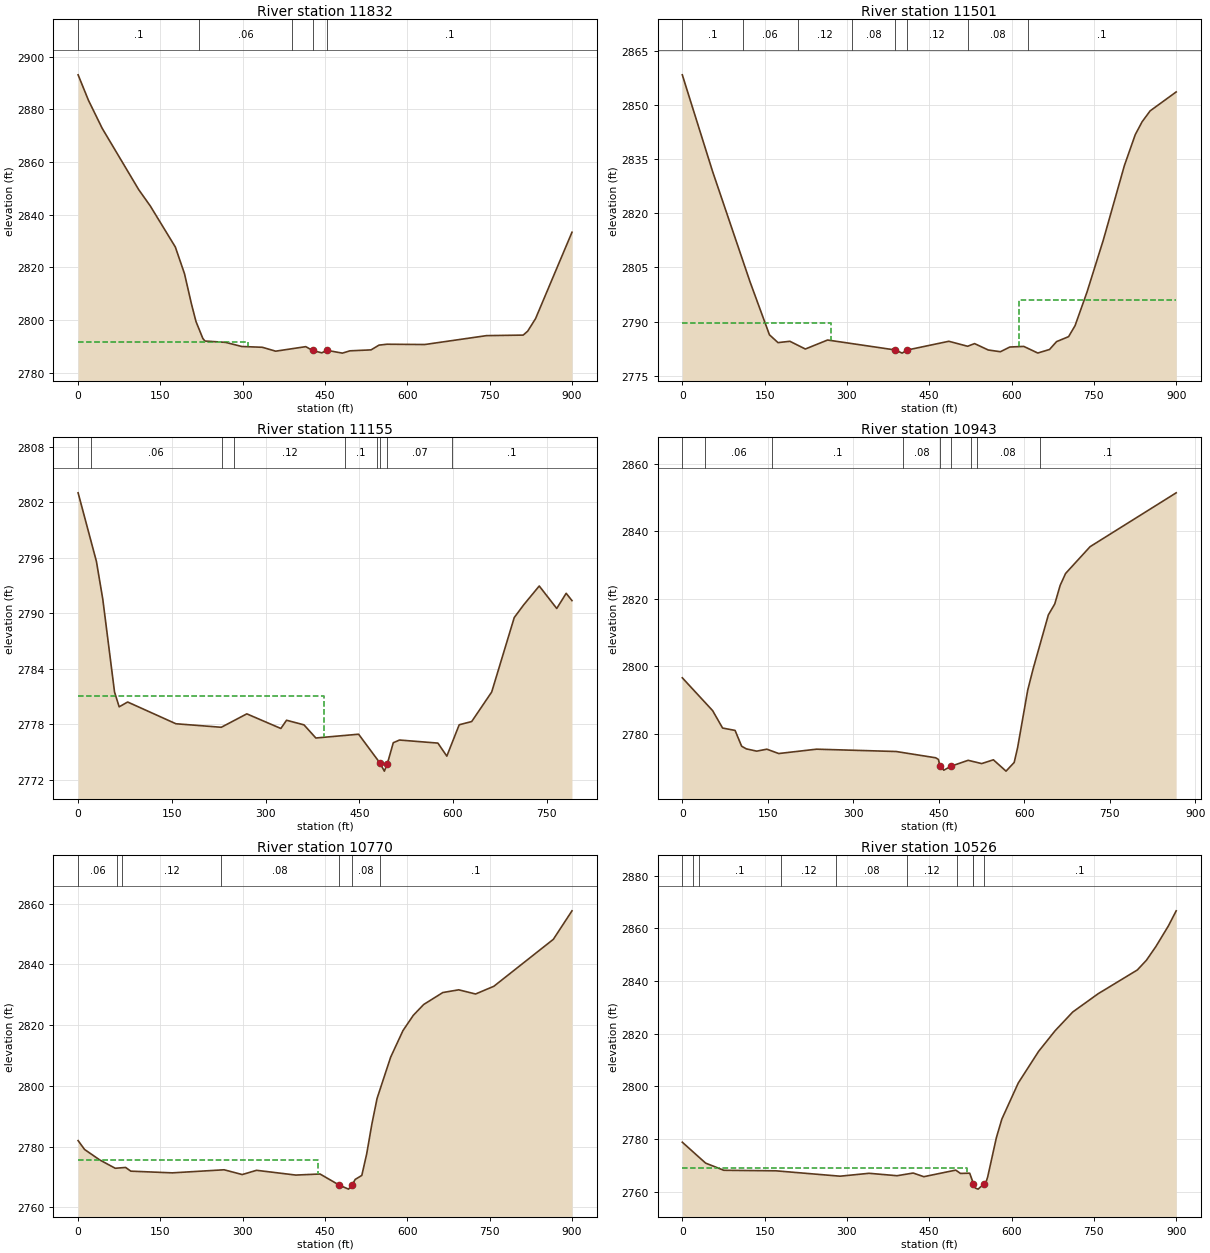
Type RM Length L Ch R = 1 ,11832   ,328.3,331,330.6
XS GIS Cut Line= 2
2319645.05186876543215.1343571342319391.17548987544078.584867727
#Sta/Elev= 30
       0 2893.14    18.8 2883.49    43.8 2872.84   110.5 2849.49   131.7 2843.25
   177.2  2827.7   193.9 2817.54   206.4 2806.19   214.8  2799.4   227.3 2792.96
   231.1 2791.98     269 2791.46   298.2  2789.9   335.7  2789.6     360 2788.12
   414.9 2789.84   427.4 2788.38   444.1 2787.49   453.4 2788.44   481.6 2787.38
   495.3 2788.25     534 2788.62   548.3 2790.42     563 2790.76   631.7 2790.65
   744.3 2794.03   811.1 2794.23   819.3 2795.73   833.6 2800.49     900 2833.32
#Mann= 5 ,-1,0
       0      .1       0     220     .06       0     390      .1       0
   427.4    .045       0   453.4      .1       0
#XS Ineff= 2 , 0
          310.16 2791.44
Permanent Ineff=
       F       F
Bank Sta=427.4,453.4
XS Rating Curve= 0 ,0
Exp/Cntr(USF)=0,0
Exp/Cntr=0.3,0.1

Type RM Length L Ch R = 1 ,11501   ,343.9,346,354.1
XS GIS Cut Line= 2
2319376.16879833543129.2672143622319064.84511124543973.706413981
#Sta/Elev= 30
       0 2858.37    55.3 2831.55   123.5    2801   158.8 2786.36   174.4 2784.19
     196 2784.56   224.2 2782.42   264.7 2784.91   387.9 2782.16   400.6 2781.28
   409.2 2782.12   485.7 2784.56     520 2783.18   532.6 2783.92   557.5 2782.15
   579.7 2781.67   596.8 2782.97   622.3 2783.14   647.8 2781.31   669.2 2782.29
     682 2784.47   703.9 2785.84   715.7 2788.88   737.4 2798.15   767.3 2812.65
   805.6 2833.23   825.4 2841.79   837.8 2845.34   852.5 2848.38     900 2853.63
#Mann= 8 ,-1,0
       0      .1       0     110     .06       0     210     .12       0
     310     .08       0   387.9    .045       0   409.2     .12       0
     520     .08       0     630      .1       0
#XS Ineff= 2 , 0
          271.55 2789.69  612.96            2796
Permanent Ineff=
       F       F
Bank Sta=387.9,409.2
XS Rating Curve= 0 ,0
Exp/Cntr(USF)=0,0
Exp/Cntr=0.3,0.1

Type RM Length L Ch R = 1 ,11155   ,213.1,211.9,212.8
XS GIS Cut Line= 4
2319151.78509083543107.3459716722318987.08390764543413.692795125
 2318842.7001982543636.979132761 2318836.7638627543813.577462054
#Sta/Elev= 30
       0    2803    29.3 2795.59    39.5  2791.5    58.3 2781.47    65.7 2779.87
    79.3 2780.39   156.5 2778.04   229.2 2777.66     270 2779.11   324.5 2777.53
   333.6 2778.42   361.5 2777.92   380.5  2776.5   448.9 2776.91   482.6 2773.84
   490.1 2772.92   494.9 2773.72   504.4 2775.99   514.4 2776.28   575.8 2775.95
   590.1 2774.54   609.9 2777.93   629.9 2778.28   661.9 2781.47     698 2789.52
   713.2  2790.9     738 2792.93     766  2790.5   781.1 2792.14   790.4 2791.35
#Mann= 9 ,-1,0
       0      .1       0      20     .06       0     230      .1       0
     250     .12       0  427.81      .1       0  477.81     .07       0
   482.6    .045       0   494.9     .07       0  597.81      .1       0
#XS Ineff= 2 , 0
          393.92 2781.08
Permanent Ineff=
       F       F
Bank Sta=482.6,494.9
XS Rating Curve= 0 ,0
Exp/Cntr(USF)=0,0
Exp/Cntr=0.3,0.1

Type RM Length L Ch R = 1 ,10943   ,168.7,172.7,168.7
XS GIS Cut Line= 4
2319080.12300477543066.3675368392318958.05215149543101.768084291
2318640.66793296543597.375748618 2318623.5780135543747.522898155
#Sta/Elev= 30
       0 2796.57    53.2 2786.83    70.7 2781.66    92.6 2780.96   104.1 2776.28
   112.4 2775.48   130.6 2774.81   148.3 2775.39   169.2  2774.1   235.6 2775.39
   375.3  2774.7   444.6 2772.84   449.4 2772.35   452.3 2770.37   458.9 2769.16
   471.8 2770.35   501.6 2772.09   525.4 2771.12   545.9 2772.24   568.1 2768.88
   582.4 2771.45   588.4 2775.82   606.1 2792.86   615.6  2799.2   642.4 2815.24
   653.6 2818.48   663.1 2823.99   672.6 2827.52   715.6 2835.47   866.7 2851.45
#Mann= 9 ,-1,0
       0      .1       0      40     .06       0   157.1      .1       0
   387.1     .08       0   452.3    .045       0   471.8     .08       0
   507.1      .1       0   517.1     .08       0   627.1      .1       0
Bank Sta=452.3,471.8
XS Rating Curve= 0 ,0
Exp/Cntr(USF)=0,0
Exp/Cntr=0.3,0.1

Type RM Length L Ch R = 1 ,10770   ,242.2,244.3,245.5
XS GIS Cut Line= 2
2318883.20141438542959.883917494 2318404.4077944543721.957844003
#Sta/Elev= 30
       0 2781.96    11.8 2779.04    39.3 2775.61    67.7 2772.85    86.6 2773.12
      96  2771.9   171.6 2771.34   266.1 2772.35   299.1 2770.78   325.2 2772.18
   396.7 2770.61   440.9 2770.96     476 2767.29   492.8 2765.98   499.2 2767.38
     505 2769.18     517  2770.5   525.9  2777.6   535.3 2787.38   544.8 2795.86
   569.6 2809.47     592 2818.21   610.9 2823.25   629.8 2826.81   664.6 2830.74
   693.6 2831.64   724.3 2830.26   757.6  2832.8     866 2848.27     900 2857.66
#Mann= 7 ,-1,0
       0     .06       0      70      .1       0      80     .12       0
     260     .08       0     476    .045       0   499.2     .08       0
     550      .1       0
#XS Ineff= 2 , 0
          436.62 2775.61
Permanent Ineff=
       F       F
Bank Sta=476,499.2
XS Rating Curve= 0 ,0
Exp/Cntr(USF)=0,0
Exp/Cntr=0.3,0.1

Type RM Length L Ch R = 1 ,10526   ,266.7,269.3,267.8
XS GIS Cut Line= 2
2318760.46638124542805.726083207 2318203.6430246543512.795916741
#Sta/Elev= 30
       0 2778.78    42.5 2770.84    75.7 2768.12   170.7 2767.92   287.5 2765.88
   340.4 2766.98   391.3 2766.06   420.7 2767.08   440.1 2765.69   498.3 2768.19
   506.8 2766.93   523.7 2767.02   530.6 2763.03   533.9 2761.39     539 2760.97
   549.5  2762.9   554.3 2764.13   556.5 2765.61   572.3 2780.47   582.3 2787.55
   612.2 2801.25   649.2 2813.24   679.3 2821.09   711.6 2828.23   757.9 2835.16
   829.2 2844.17   845.8 2847.87   862.9 2853.03   885.7 2860.85     900 2866.62
#Mann= 10 ,-1,0
       0     .06       0      20     .05       0      30      .1       0
     180     .12       0     280     .08       0     410     .12       0
     500     .08       0     530      .1       0   530.6    .045       0
   549.5      .1       0
#XS Ineff= 2 , 0
          519.57 2768.93
Permanent Ineff=
       F       F
Bank Sta=530.6,549.5
XS Rating Curve= 0 ,0
Exp/Cntr(USF)=0,0
Exp/Cntr=0.3,0.1