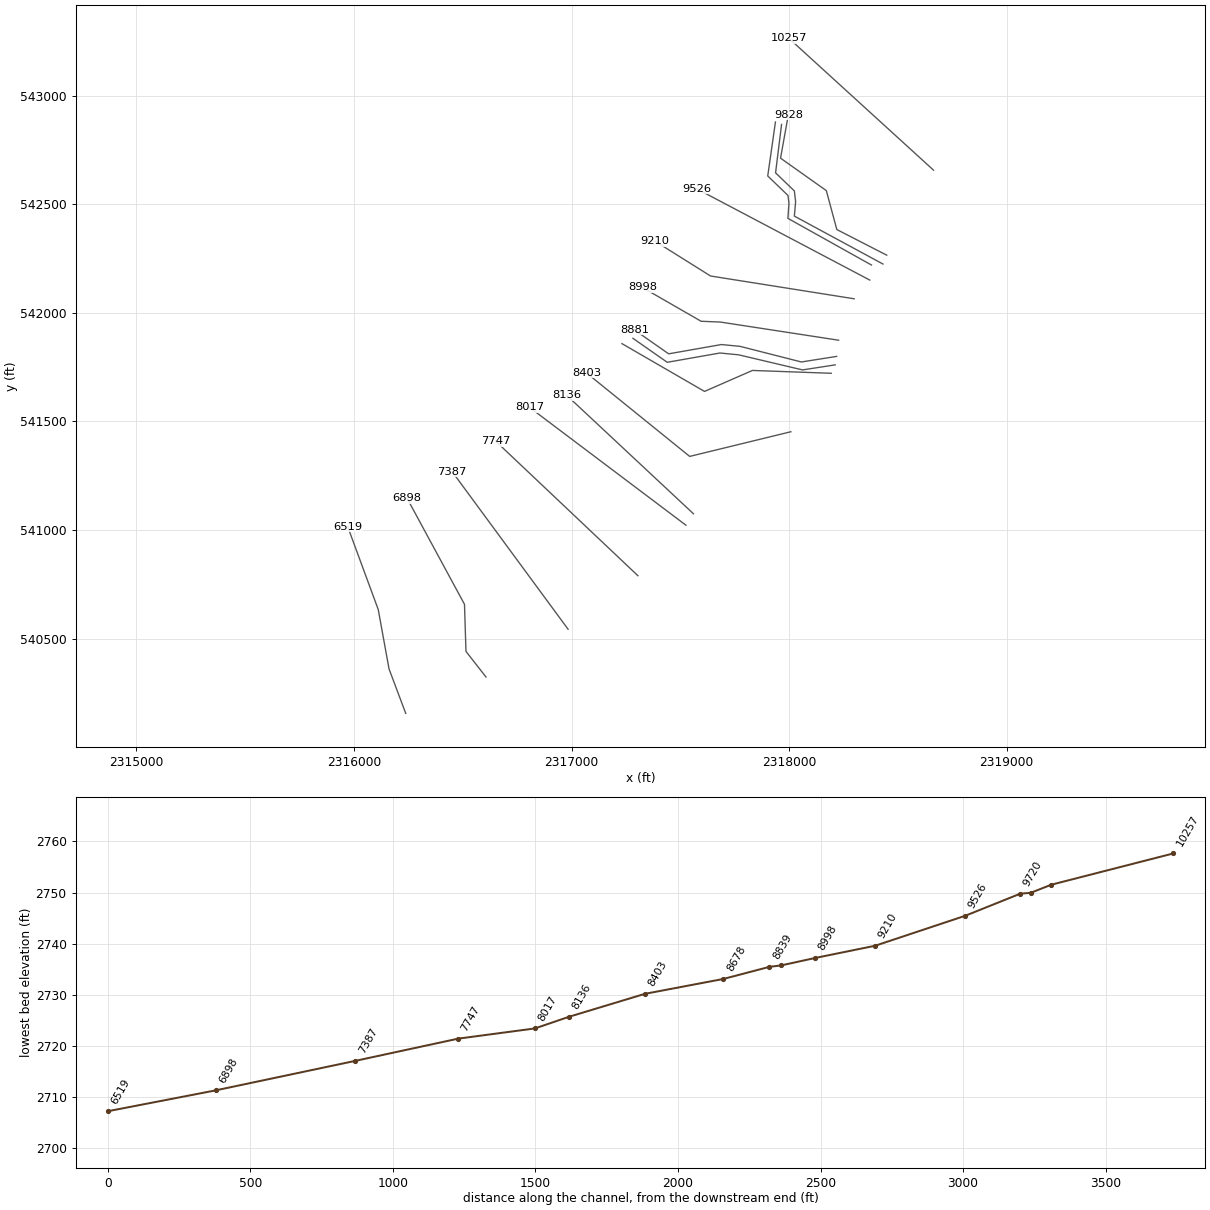
HEC-RAS study SLSBRYRN.prj: SLSBRYRN

--- SLSBRYRN.g01 (geometry) --- (continued)

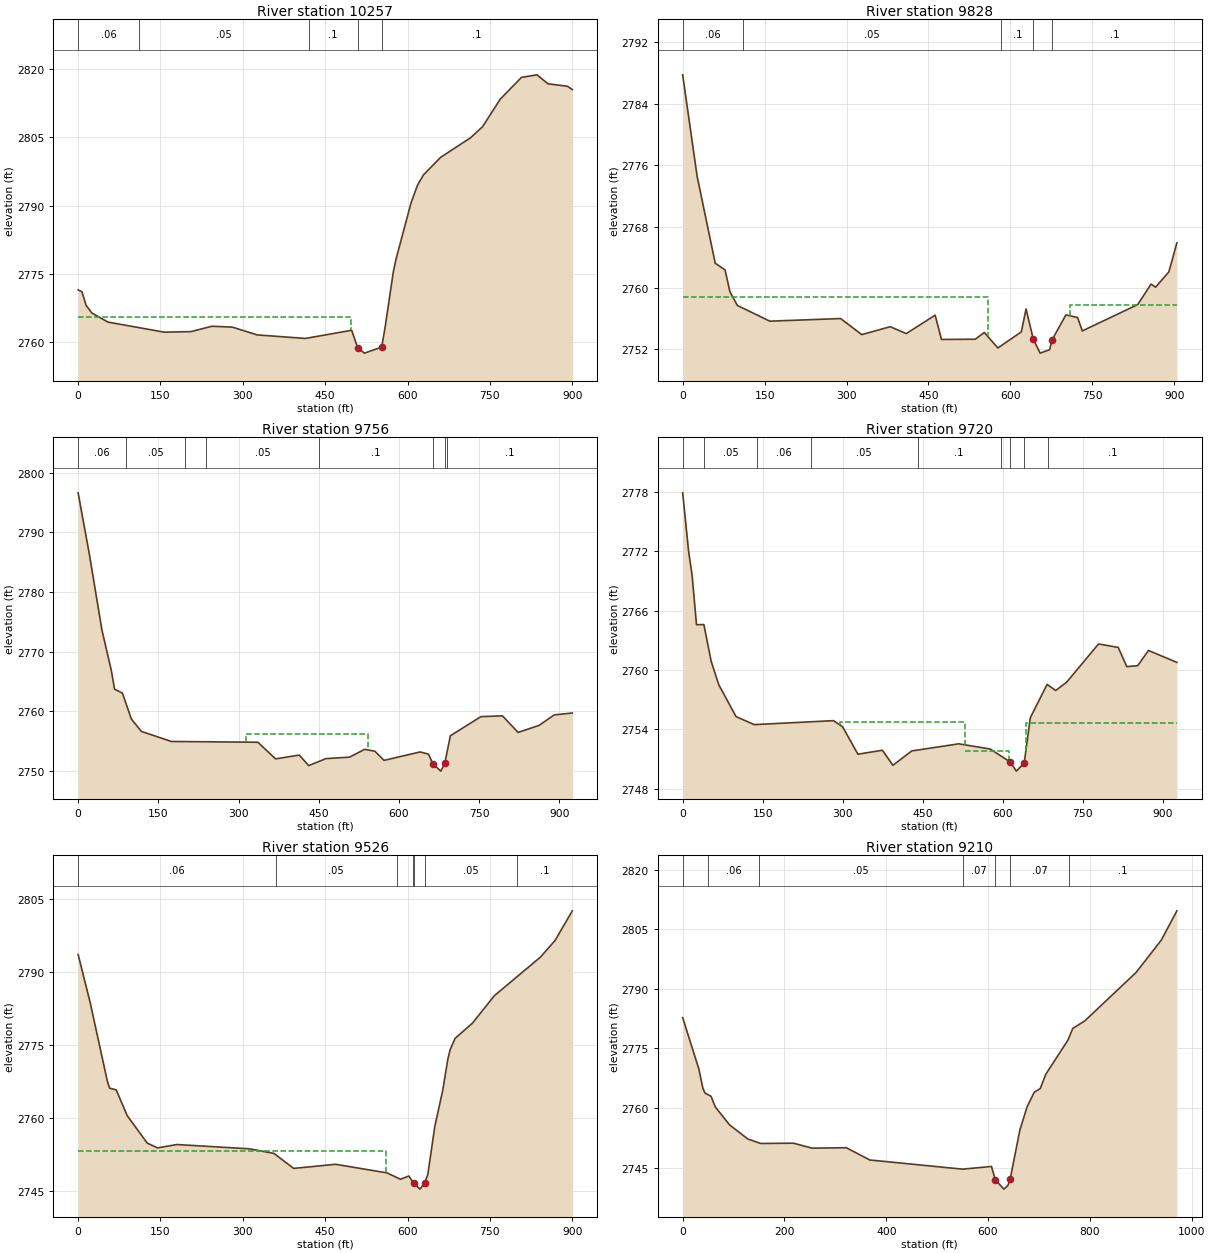
Type RM Length L Ch R = 1 ,10257   ,426.5,428.7,432.2
XS GIS Cut Line= 2
2318664.12845828542656.4751631062317999.39420227543263.210994328
#Sta/Elev= 30
       0 2771.53       7 2771.12    14.6 2768.13    24.8 2766.48    54.4 2764.46
     157 2762.25   205.7 2762.37   243.6 2763.55   280.8 2763.36   326.1 2761.65
   413.8 2760.87   498.2 2762.67     509 2758.83   521.4 2757.65   552.8 2758.96
   558.8 2763.12     574 2775.49   579.4 2778.49   606.2  2790.6   618.1 2794.52
     629 2796.78   660.2 2800.62   714.8 2804.93   736.5 2807.34     769 2813.43
   807.4 2818.17   835.7 2818.73   855.6 2816.76   891.1 2816.22     900 2815.49
#Mann= 5 ,-1,0
       0     .06       0     110     .05       0     420      .1       0
     509    .045       0   552.8      .1       0
#XS Ineff= 2 , 0
           496.9 2765.51
Permanent Ineff=
       F       F
Bank Sta=509,552.8
XS Rating Curve= 0 ,0
Exp/Cntr(USF)=0,0
Exp/Cntr=0.3,0.1

Type RM Length L Ch R = 1 ,9828    ,74.6,72.3,70.4
BEGIN DESCRIPTION:
structure xs 4
END DESCRIPTION:
XS GIS Cut Line= 5
2318449.16500863542265.1182677842318219.63587675542383.100531832
2318171.37040509542562.219059977 2317960.8889868542711.699838797
2317996.76902613542911.634851077
#Sta/Elev= 30
       0 2787.74    26.4 2774.55    59.6 2763.22    77.6 2762.35    86.6 2759.49
   100.1 2757.73   159.5 2755.68   289.2 2756.02   327.9 2753.93   380.1 2754.96
   409.4 2754.06   462.3 2756.46   473.8  2753.3   535.8 2753.33   552.3 2754.21
   577.1 2752.19   620.1 2754.29   628.7 2757.27   642.1 2753.32   654.5 2751.52
   671.8 2751.96   676.7 2753.28   701.7  2756.5   723.1 2756.15   731.7 2754.41
   833.2 2757.84   857.7 2760.51   865.8  2760.1   890.2 2762.09   904.9 2765.87
#Mann= 5 ,-1,0
       0     .06       0     110     .05       0  583.58      .1       0
   642.1    .045       0   676.7      .1       0
#XS Ineff= 2 , 0
          558.14 2758.88   709.3         2757.77
Permanent Ineff=
       F       F
Bank Sta=642.1,676.7
XS Rating Curve= 0 ,0
Exp/Cntr(USF)=0,0
Exp/Cntr=0.5,0.3

Type RM Length L Ch R = 1 ,9756    ,36.5,35.8,35.8
BEGIN DESCRIPTION:
structure xs 3; 11.7 ft between structure and xs
END DESCRIPTION:
XS GIS Cut Line= 6
  2318431.700433542224.3757423142318024.41768315542444.963734185
2318030.20953974542511.5700850692318024.41768315542560.800866158
2317938.03447985542644.0973156232317965.58268378542866.820876221
#Sta/Elev= 30
       0 2796.66    20.9 2786.41    44.5 2773.63    62.2 2766.78    68.1 2763.69
    82.9 2763.02    99.5 2758.68   118.3  2756.6   174.3 2754.91   336.1 2754.78
   369.1 2751.99   413.4 2752.62   431.1 2750.86   463.4 2752.03   507.6 2752.28
   535.7 2753.59   554.9 2753.27   571.9 2751.74   639.5 2753.15   655.1 2752.78
   663.3 2751.15   678.1 2749.93   685.5 2751.22     696 2755.87   753.1 2759.08
   793.4 2759.21   822.6 2756.43   861.9 2757.61   890.1 2759.37     924 2759.69
#Mann= 8 ,-1,0
       0     .06       0      90     .05       0     200     .06       0
     240     .05       0     450      .1       0   663.3    .045       0
   685.5     .05       0  689.61      .1       0
#XS Ineff= 3 ,-1
  313.95  541.53 2756.24  541.53     651  2751.8     697     924  2754.6
Permanent Ineff=
       F       F       F
Bank Sta=663.3,685.5
XS Rating Curve= 0 ,0
Exp/Cntr(USF)=0,0
Exp/Cntr=0.5,0.3

Type RM Length L Ch R = 1 ,9720    ,188.9,193.3,198.1
BEGIN DESCRIPTION:
structure xs 2; 11.7 ft between structure and xs
END DESCRIPTION:
XS GIS Cut Line= 6
2318378.81682155542219.791589188 2317994.7014981542434.587724459
2317999.52804526542504.0900036442317995.12130219542539.974054326
2317902.03992225542629.6612144222317937.41582037542877.987677115
#Sta/Elev= 30
       0  2777.9      11 2772.04    17.7 2769.55    25.9 2764.57    39.7 2764.59
    53.4 2760.88    67.6 2758.51     100 2755.29     134 2754.48   282.6 2754.88
   299.8 2754.25   328.4 2751.49   374.2 2751.89   393.9 2750.37   429.2 2751.82
   517.3 2752.54   576.5 2752.01   613.9 2750.69   625.2 2749.78   639.9  2750.6
   651.4 2755.18   682.8 2758.54   698.9 2757.93   719.2 2758.75   779.2 2762.63
   816.1 2762.28   832.1 2760.34   852.5 2760.43   872.7 2761.97     926 2760.77
#Mann= 9 ,-1,0
       0     .06       0      40     .05       0     140     .06       0
     240     .05       0     440      .1       0  595.92     .05       0
   613.9    .045       0   639.9     .05       0  685.18      .1       0
#XS Ineff= 3 ,-1
  294.02  528.24 2754.73  528.24     611  2751.8     643     926  2754.6
Permanent Ineff=
       F       F       F
Bank Sta=613.9,639.9
XS Rating Curve= 0 ,0
Exp/Cntr(USF)=0,0
Exp/Cntr=0.5,0.3

Type RM Length L Ch R = 1 ,9526    ,310,317,322.6
BEGIN DESCRIPTION:
structure xs 1
END DESCRIPTION:
XS GIS Cut Line= 2
 2318371.2284586542150.4258402232317575.39362843542570.719693477
#Sta/Elev= 30
       0 2793.55    22.1 2783.61    53.2 2767.59    57.3 2766.14    69.4 2765.79
    89.4 2760.51   125.8 2754.89   144.5  2753.9   179.9 2754.59   312.2 2753.71
   356.6 2752.77   392.5  2749.7   469.1 2750.54   562.6 2748.78     587 2747.47
   602.3 2748.13   611.1 2746.64   622.6 2745.45   631.2 2746.78   636.8 2748.42
   649.6 2758.33   663.9 2765.63   673.3 2772.09   677.5 2774.03   686.5 2776.35
   718.2 2779.48     758 2785.09     842 2793.01   868.7 2796.44     900 2802.49
#Mann= 7 ,-1,0
       0     .06       0     360     .05       0     580      .1       0
     610     .05       0   611.1    .045       0   631.2     .05       0
     800      .1       0
#XS Ineff= 2 , 0
           559.8 2753.32
Permanent Ineff=
       F       F
Bank Sta=611.1,631.2
XS Rating Curve= 0 ,0
Exp/Cntr(USF)=0,0
Exp/Cntr=0.3,0.1

Type RM Length L Ch R = 1 ,9210    ,211.3,211.3,212.7
XS GIS Cut Line= 3
2318299.34262977542064.3994482392317639.11864713542169.272571837
2317382.89453834542330.157477356
#Sta/Elev= 30
       0 2782.76    31.6  2769.9    39.7 2764.99    43.7  2763.8    55.8 2762.94
      64 2760.28    92.3 2755.73   128.1 2752.19   153.1 2751.07   217.9 2751.14
   254.3 2749.89   321.5    2750   367.7 2746.91     550  2744.6   606.7 2745.28
   614.4 2741.93     631 2739.57   639.1  2740.5   643.3 2742.01   662.5 2754.46
   676.7  2760.3   690.8 2763.99   702.5  2764.9   713.5 2768.52     757 2777.11
   766.4 2780.04   790.1 2781.95   891.1 2794.18   940.4  2802.3     971 2809.67
#Mann= 7 ,-1,0
       0     .12       0      50     .06       0     150     .05       0
     550     .07       0   614.4    .045       0   643.3     .07       0
   758.5      .1       0
Bank Sta=614.4,643.3
XS Rating Curve= 0 ,0
Exp/Cntr(USF)=0,0
Exp/Cntr=0.3,0.1

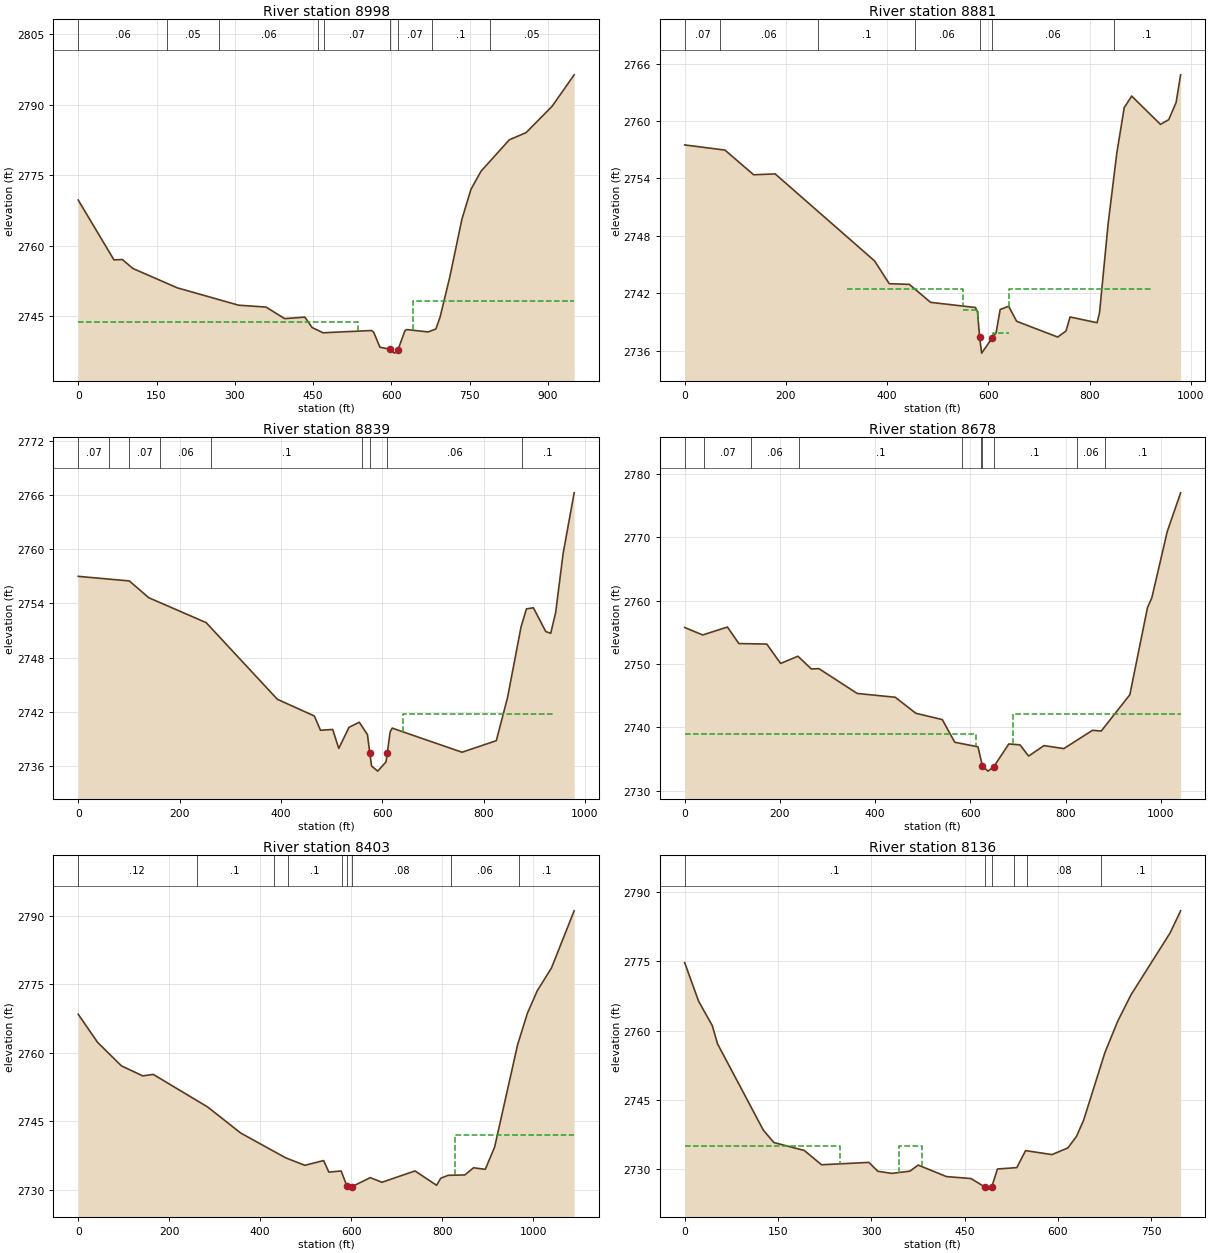
Type RM Length L Ch R = 1 ,8998    ,113.9,117.1,121.3
BEGIN DESCRIPTION:
structure xs 4
END DESCRIPTION:
XS GIS Cut Line= 4
2318227.83653528541873.7031637012317684.00515074541957.335425333
2317595.81638772541960.9106454562317325.73131724542116.494561139
#Sta/Elev= 30
       0 2769.74    68.5 2757.01    84.6 2757.08   104.9 2755.17   189.9 2751.06
   307.2 2747.37   359.8 2746.97   395.6 2744.51   434.2 2744.83   448.2 2742.61
   469.1  2741.5   562.1 2741.98   566.1 2741.61   578.1 2738.43   598.1 2737.98
   606.1 2737.17   612.8 2737.92   626.1 2741.97   629.5 2742.18   670.4 2741.68
   685.3 2742.31   693.5 2744.91   711.9 2753.35   735.2 2765.68   752.6 2772.05
   771.9 2775.89   825.9 2782.55   858.1 2784.08   907.9 2789.68   950.2 2796.38
#Mann= 9 ,-1,0
       0     .06       0     170     .05       0     270     .06       0
     460     .05       0     470     .07       0   598.1    .045       0
   612.8     .07       0  678.49      .1       0  788.49     .05       0
#XS Ineff= 2 , 0
          536.68 2743.84   641.2         2748.27
Permanent Ineff=
       F       F
Bank Sta=598.1,612.8
XS Rating Curve= 0 ,0
Exp/Cntr(USF)=0,0
Exp/Cntr=0.5,0.3

Type RM Length L Ch R = 1 ,8881    ,40.3,41.9,40.6
BEGIN DESCRIPTION:
structure xs 3; 6.5 ft between structure and xs
END DESCRIPTION:
XS GIS Cut Line= 6
2318218.78326639541799.2043579872318056.73136921541773.548837063
2317774.69656785541845.4310354952317688.89128491541853.773215781
2317446.56046828541811.0224405712317288.90174448541921.319245295
#Sta/Elev= 30
       0 2757.51    79.6 2756.97   136.3 2754.39   178.8 2754.48   375.2 2745.38
   404.1    2743   443.8 2742.93   485.8 2741.05   574.6 2740.51   578.6 2740.03
   582.7  2737.4   586.7 2735.74   608.1 2737.36   615.2 2737.85   623.3  2740.3
   640.1 2740.64   655.8 2739.07     737 2737.42   753.3 2738.05   761.4 2739.52
   814.7 2738.92   819.6 2739.96   836.6 2749.27   853.8 2756.68   868.4 2761.41
   883.1 2762.62     940 2759.66   956.3 2760.15   970.9 2761.95   979.8 2764.84
#Mann= 7 ,-1,0
       0     .07       0      70     .06       0  264.07      .1       0
  454.07     .06       0   582.7    .045       0   608.1     .06       0
   847.4      .1       0
#XS Ineff= 5 ,-1
  320.56     550  2742.4     550     580  2740.2     610  641.13  2737.8
  641.13  922.25  2742.4  922.25   979.8  2737.8
Permanent Ineff=
       F       F       F       F       F
Bank Sta=582.7,608.1
XS Rating Curve= 0 ,0
Exp/Cntr(USF)=0,0
Exp/Cntr=0.5,0.3

Type RM Length L Ch R = 1 ,8839    ,173.7,160.8,145
BEGIN DESCRIPTION:
structure xs 2; 11.2 ft between structure and xs
END DESCRIPTION:
XS GIS Cut Line= 6
2318212.22730787541760.2574110362318062.09281109541736.985370194
2317768.14060933541806.4840885452317682.33532638541814.826268831
2317440.00450975 541772.075493622317282.34578596541882.372298344
#Sta/Elev= 30
       0    2757   100.9 2756.49   139.4 2754.63   252.5 2751.88     393  2743.4
     466 2741.55   478.1 2739.97   502.2 2740.06   514.2 2737.96   534.3 2740.29
   554.6 2740.86   570.8 2739.49   575.3 2737.51   578.9 2736.01   591.1 2735.45
   607.4 2736.47   609.9 2737.42   615.5 2739.77   619.6 2740.21   757.5 2737.54
   825.1 2738.82   847.3  2743.6   873.9 2751.41   884.6  2753.4   898.3 2753.52
   922.7 2750.89   932.5  2750.7   942.3 2753.03   956.9 2759.52   978.7 2766.24
#Mann= 9 ,-1,0
       0     .07       0      60     .06       0     100     .07       0
  161.93     .06       0  261.93      .1       0  560.19     .06       0
   575.3    .045       0   609.9     .06       0  876.27      .1       0
#XS Ineff= 4 ,-1
       0     564  2739.6     621  641.13  2737.8  641.13   936.9 2741.72
   936.9   978.7  2737.8
Permanent Ineff=
       F       F       F       F
Bank Sta=575.3,609.9
XS Rating Curve= 0 ,0
Exp/Cntr(USF)=0,0
Exp/Cntr=0.5,0.3

Type RM Length L Ch R = 1 ,8678    ,277.1,275,272.4
BEGIN DESCRIPTION:
structure xs 1
END DESCRIPTION:
XS GIS Cut Line= 4
2318193.92192915541721.4940390092317831.90008981541734.599211693
2317611.42818225541638.0682683822317231.93041215541857.879576527
#Sta/Elev= 30
       0 2755.78    37.8  2754.6    89.8 2755.85   113.8 2753.24   172.4 2753.16
   201.5  2750.1   237.9 2751.24   265.9 2749.23   281.9 2749.28   362.3 2745.36
   442.1 2744.76   485.5 2742.23     541 2741.23   567.2 2737.65   615.9 2736.93
   625.2 2733.93   636.9 2733.09   648.6 2733.73   680.7 2737.38   704.2 2737.24
   722.3 2735.47   754.6 2737.12   796.2 2736.65   856.5 2739.54   874.8 2739.42
   934.9 2745.16   971.9 2758.92   981.1 2760.49  1013.5 2770.95  1041.5 2777.05
#Mann= 10 ,-1,0
       0      .1       0      40     .07       0     140     .06       0
     240      .1       0  582.26     .08       0  622.94      .1       0
   625.2    .045       0   648.6      .1       0  822.94     .06       0
  882.94      .1       0
#XS Ineff= 2 , 0
          611.95 2738.89   689.7         2742.06
Permanent Ineff=
       F       F
Bank Sta=625.2,648.6
XS Rating Curve= 0 ,0
Exp/Cntr(USF)=0,0
Exp/Cntr=0.3,0.1

Type RM Length L Ch R = 1 ,8403    ,265.4,267,263.7
XS GIS Cut Line= 3
2318008.35263444541452.3982892572317543.26268343541338.872395705
2317068.40706416541723.395583544
#Sta/Elev= 30
       0 2768.44    42.5  2762.3    94.9 2757.15   141.8 2754.95   164.9 2755.28
   284.6 2748.14   356.9 2742.46   456.2 2737.01   498.2 2735.39   539.3 2736.43
   550.8  2733.9   577.8 2734.15   590.7  2730.8   596.3 2730.18     602 2730.75
   641.8 2732.69   667.4 2731.68   740.1 2734.16   787.5 2731.02   796.7 2732.56
   812.9  2733.2   849.5 2733.28   868.7 2734.85   894.5 2734.51   915.1  2739.4
   965.5 2761.75   987.1 2768.67  1008.7 2773.57    1040 2778.57  1089.8 2791.06
#Mann= 9 ,-1,0
       0     .12       0     260      .1       0     430     .12       0
     460      .1       0  578.75     .08       0   590.7    .045       0
     602     .08       0  818.75     .06       0  968.75      .1       0
#XS Ineff= 2 , 0
                          827.24         2741.95
Permanent Ineff=
       F       F
Bank Sta=590.7,602
XS Rating Curve= 0 ,0
Exp/Cntr(USF)=0,0
Exp/Cntr=0.3,0.1

Type RM Length L Ch R = 1 ,8136    ,118.4,119.6,120.6
XS GIS Cut Line= 2
2317560.50198414541074.8866226832316978.38528132541619.510808305
#Sta/Elev= 30
       0 2774.74    22.4 2766.39    44.3 2761.12    52.8 2757.16   126.4 2738.46
   143.4 2735.77   192.2 2734.06     220 2730.96   296.2 2731.47   310.3 2729.55
     333 2729.09     362 2729.57   375.4 2730.89   420.7  2728.4   460.3 2727.97
   482.5 2726.14   488.6 2725.68   493.4 2726.08   502.8 2730.04   533.9 2730.34
     548 2734.02   590.5 2733.16     616 2734.61   629.8  2737.1   641.3 2740.62
   675.4 2755.22   696.1 2762.06   717.6  2767.8   780.1 2781.13   797.2 2785.96
#Mann= 6 ,-1,0
       0      .1       0   482.5    .045       0   493.4      .1       0
     530     .06       0     550     .08       0     670      .1       0
#XS Ineff= 2 ,-1
       0  249.58    2735  344.19   381.42735.009
Permanent Ineff=
       F       F
Bank Sta=482.5,493.4
XS Rating Curve= 0 ,0
Exp/Cntr(USF)=0,0
Exp/Cntr=0.3,0.1

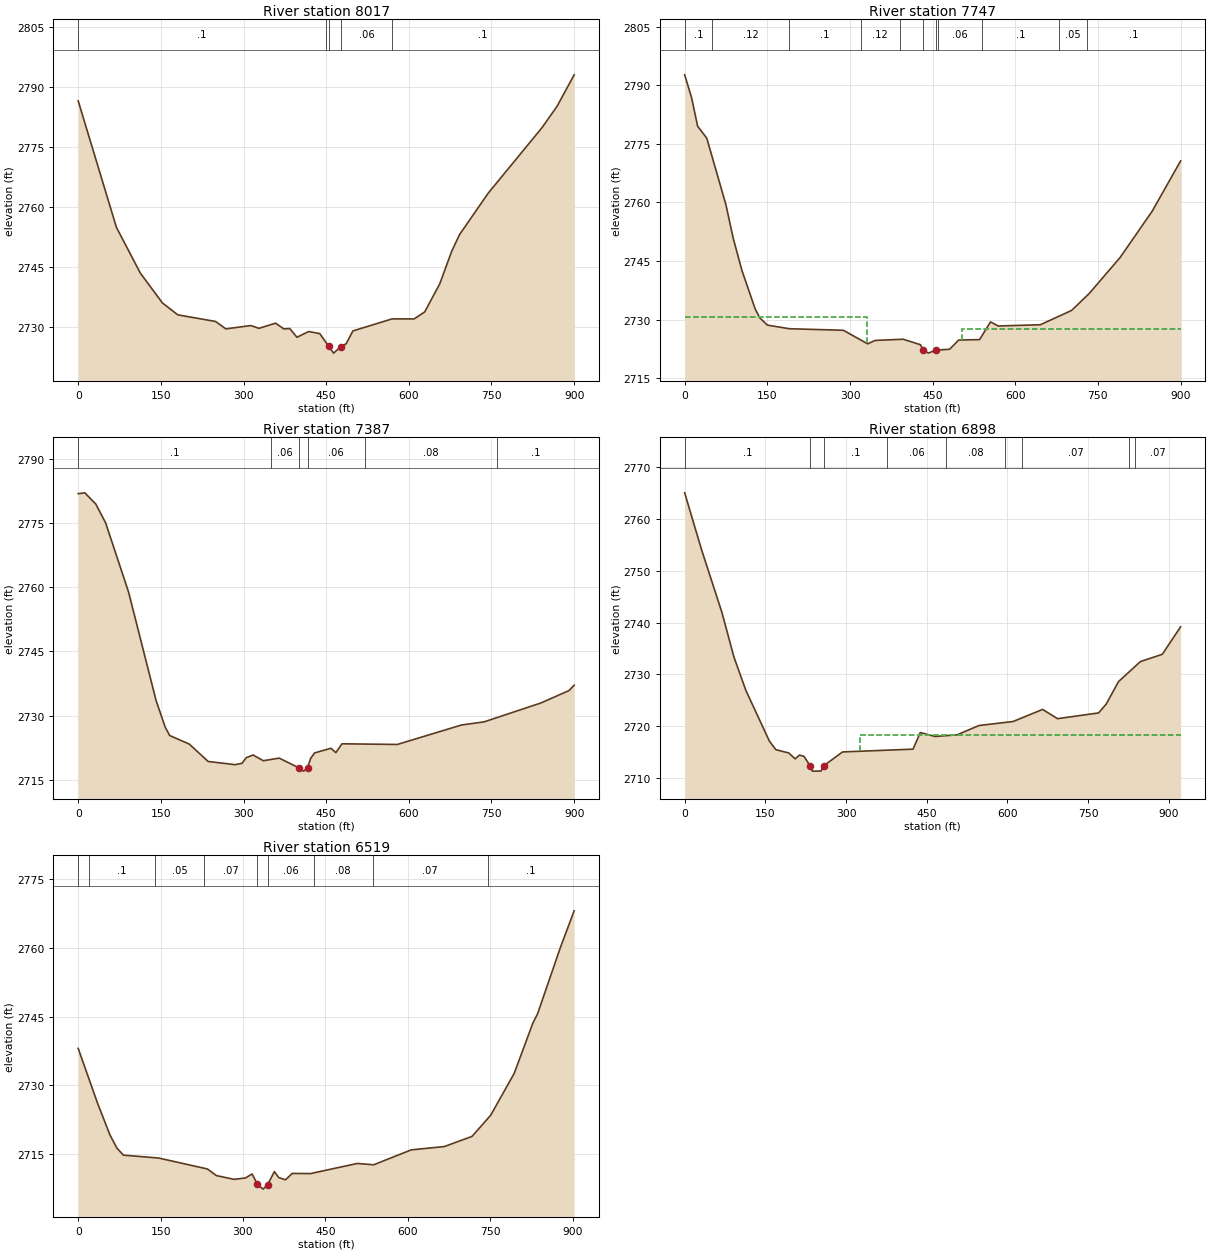
Type RM Length L Ch R = 1 ,8017    ,271.2,269.4,267.5
XS GIS Cut Line= 2
2317526.13399162541022.0725972382316807.63595372541564.069432593
#Sta/Elev= 30
       0 2786.53    69.3  2754.9   112.7 2743.44   152.8 2735.97   180.7 2732.98
   249.2 2731.33     268 2729.47   313.1  2730.3   328.1 2729.61   358.2  2730.9
   373.2 2729.46   383.8 2729.57     397 2727.38   418.3 2728.81   438.4 2728.28
  454.562725.106   463.4  2723.4   476.7 2725.02   486.3 2725.75   498.5 2728.96
   569.7 2731.97   609.6 2731.96   628.8 2733.72   656.1 2740.74   677.6 2748.83
   691.9 2753.04     744 2763.43   842.1 2779.91     869 2785.19     900 2793.06
#Mann= 5 ,-1,0
       0      .1       0     450     .06       0  454.56    .045       0
   476.7     .06       0     570      .1       0
Bank Sta=454.56,476.7
XS Rating Curve= 0 ,0
Exp/Cntr(USF)=0,0
Exp/Cntr=0.3,0.1

Type RM Length L Ch R = 1 ,7747    ,359.7,360,355.9
XS GIS Cut Line= 2
 2317305.2545248540789.7030394772316651.82691041541408.599115366
#Sta/Elev= 30
       0 2792.67    12.5 2786.84    23.5 2779.51    40.1 2776.45    74.9 2759.38
    88.1 2750.81   103.9 2742.57   127.7 2732.81   136.2 2730.44   150.2 2728.57
     190 2727.65     288 2727.25   332.1 2723.78   345.6 2724.65   396.5 2724.96
   427.6 2723.57   433.3 2722.18   442.2  2721.4   455.9 2722.17   480.8 2722.39
   497.3 2724.75   535.2 2724.86     555 2729.39     569 2728.35   645.5 2728.67
   702.1 2732.33   734.2 2736.68   790.3 2745.91   848.5 2757.77     900 2770.62
#Mann= 11 ,-1,0
       0      .1       0      50     .12       0     190      .1       0
     320     .12       0     390      .1       0   433.3    .045       0
   455.9      .1       0     460     .06       0     540      .1       0
     680     .05       0     730      .1       0
#XS Ineff= 2 , 0
          330.56 2730.54  503.66         2727.69
Permanent Ineff=
       F       F
Bank Sta=433.3,455.9
XS Rating Curve= 0 ,0
Exp/Cntr(USF)=0,0
Exp/Cntr=0.3,0.1

Type RM Length L Ch R = 1 ,7387    ,500.4,489.6,474.5
XS GIS Cut Line= 2
2316984.10731764540543.487426438 2316451.2715622541268.805327582
#Sta/Elev= 30
       0 2781.85      12 2782.05    31.9 2779.44    49.8 2775.03    91.4 2758.87
   141.4 2733.51   157.8 2727.36   165.9 2725.38   201.5 2723.38   235.8 2719.32
   284.4 2718.57   297.2 2718.88   304.9  2720.2   317.4 2720.83   335.9 2719.49
   364.7  2720.1     401 2717.79   409.1 2717.06   416.1 2717.84   421.8 2720.03
   428.9 2721.31   458.7  2722.4   467.6 2721.38   478.6 2723.44   579.2 2723.29
   695.8 2727.84   736.5 2728.56   839.5 2732.97   890.5 2735.86     900 2737.12
#Mann= 6 ,-1,0
       0      .1       0     350     .06       0     401    .045       0
   416.1     .06       0     520     .08       0     760      .1       0
Bank Sta=401,416.1
XS Rating Curve= 0 ,0
Exp/Cntr(USF)=0,0
Exp/Cntr=0.3,0.1

Type RM Length L Ch R = 1 ,6898    ,376.7,379.1,381.7
XS GIS Cut Line= 4
2316606.83968671540323.4199062622316514.81837965  540441.3820947
2316507.94601208540658.1463665812316243.63820405 541146.87888095
#Sta/Elev= 30
       0 2765.09    31.7 2753.99    69.4 2741.92    91.5 2733.38   113.8 2726.89
   157.4 2717.12   169.4 2715.44   193.4 2714.81   205.4 2713.66   213.4 2714.39
   221.8 2714.15233.51662712.262   237.5 2711.29   253.5 2711.31   258.3  2712.3
   293.5    2715   424.6 2715.54   438.1 2718.75   465.4 2717.99   506.4  2718.3
   547.3 2720.11   610.6 2720.88   665.5 2723.22   693.2 2721.43   769.6 2722.54
   783.8 2724.25   806.5 2728.58   847.4 2732.47     888 2733.87   922.1  2739.2
#Mann= 9 ,-1,0
       0      .1       0233.5166    .045       0   258.3      .1       0
  376.48     .06       0  486.48     .08       0  596.48      .1       0
  626.48     .07       0  826.48     .03       0  836.48     .07       0
#XS Ineff= 2 , 0
                          325.07         2718.32
Permanent Ineff=
       F       F
Bank Sta=233.5166,258.3
XS Rating Curve= 0 ,0
Exp/Cntr(USF)=0,0
Exp/Cntr=0.3,0.1

Type RM Length L Ch R = 1 ,6519    ,399.8,396.2,393.5
XS GIS Cut Line= 4
 2316237.8193018540156.1020397562316160.95638158540361.214124642
2316111.61834389540633.6458979882315971.03959877541015.653428593
#Sta/Elev= 30
       0 2738.01    35.3 2725.99      58 2719.02    70.5 2716.18    82.3 2714.64
   146.4 2714.01   235.3 2711.61   251.5 2710.17     284 2709.34   304.4 2709.64
   316.6 2710.52   326.4 2708.24   336.7  2707.2     345  2708.2   357.2 2711.04
   365.3 2709.71   377.5 2709.25   389.7 2710.64   422.7  2710.6   508.2 2712.82
     538 2712.53   606.2 2715.79   666.5 2716.52     717 2718.74   751.1 2723.39
   793.8 2732.53   827.9 2743.57   836.4 2745.59   878.3 2760.23     903 2768.14
#Mann= 9 ,-1,0
       0     .12       0      20      .1       0     140     .05       0
  229.04     .07       0   326.4    .045       0     345     .06       0
  429.04     .08       0   535.9     .07       0   745.9      .1       0
Bank Sta=326.4,345
XS Rating Curve= 0 ,0
Exp/Cntr(USF)=0,0
Exp/Cntr=0.3,0.1