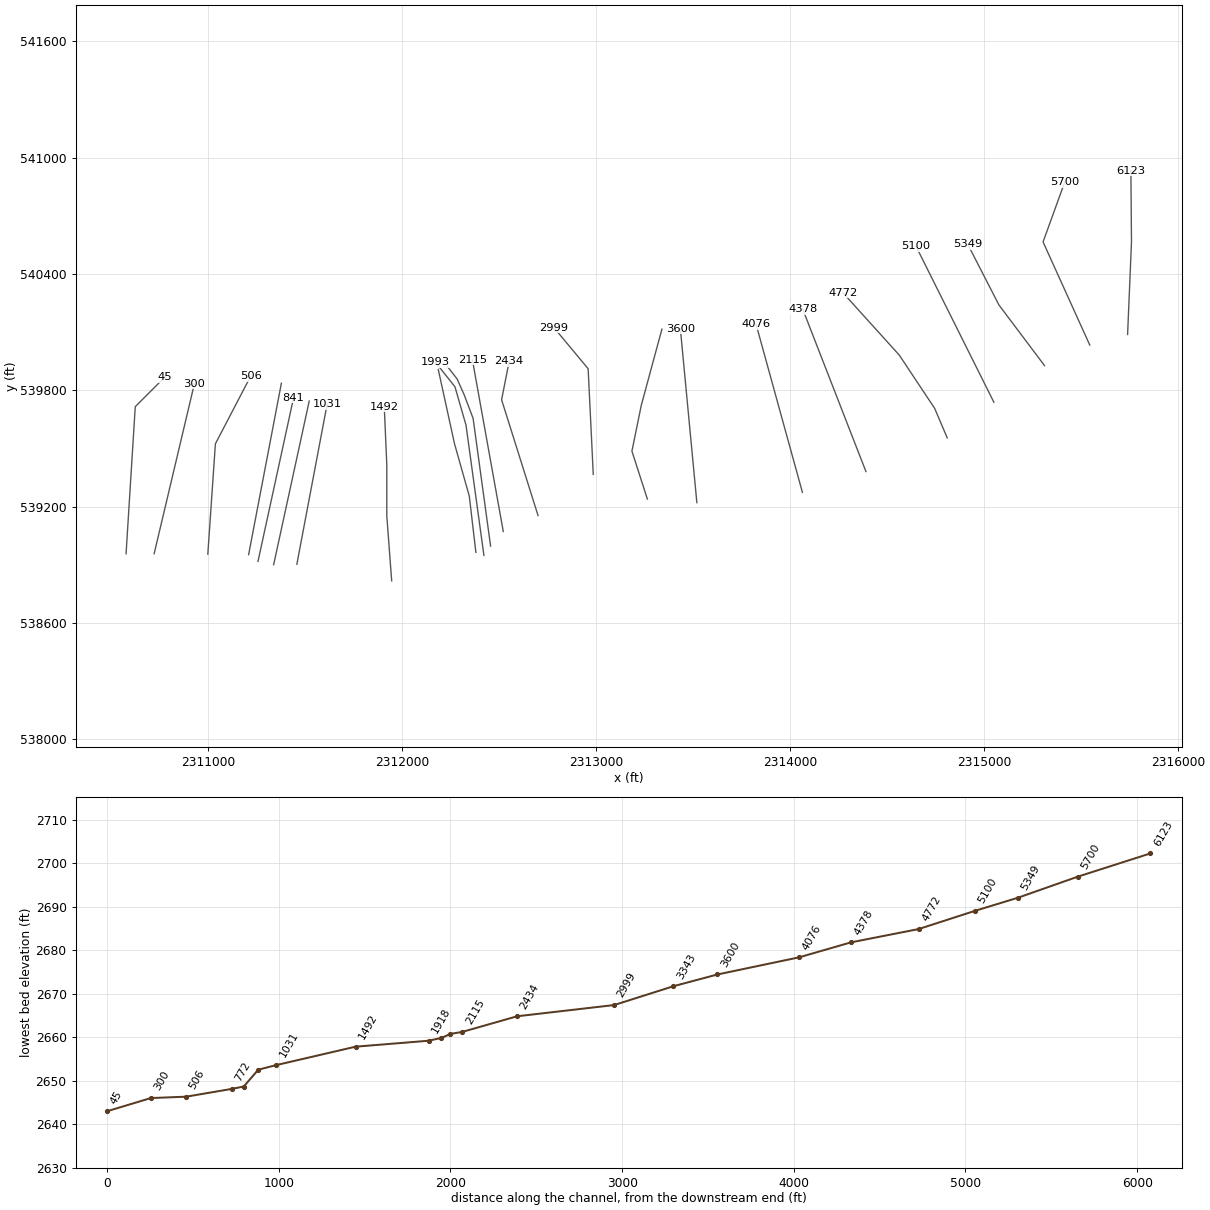
HEC-RAS study SLSBRYRN.prj: SLSBRYRN

--- SLSBRYRN.g01 (geometry) --- (continued)

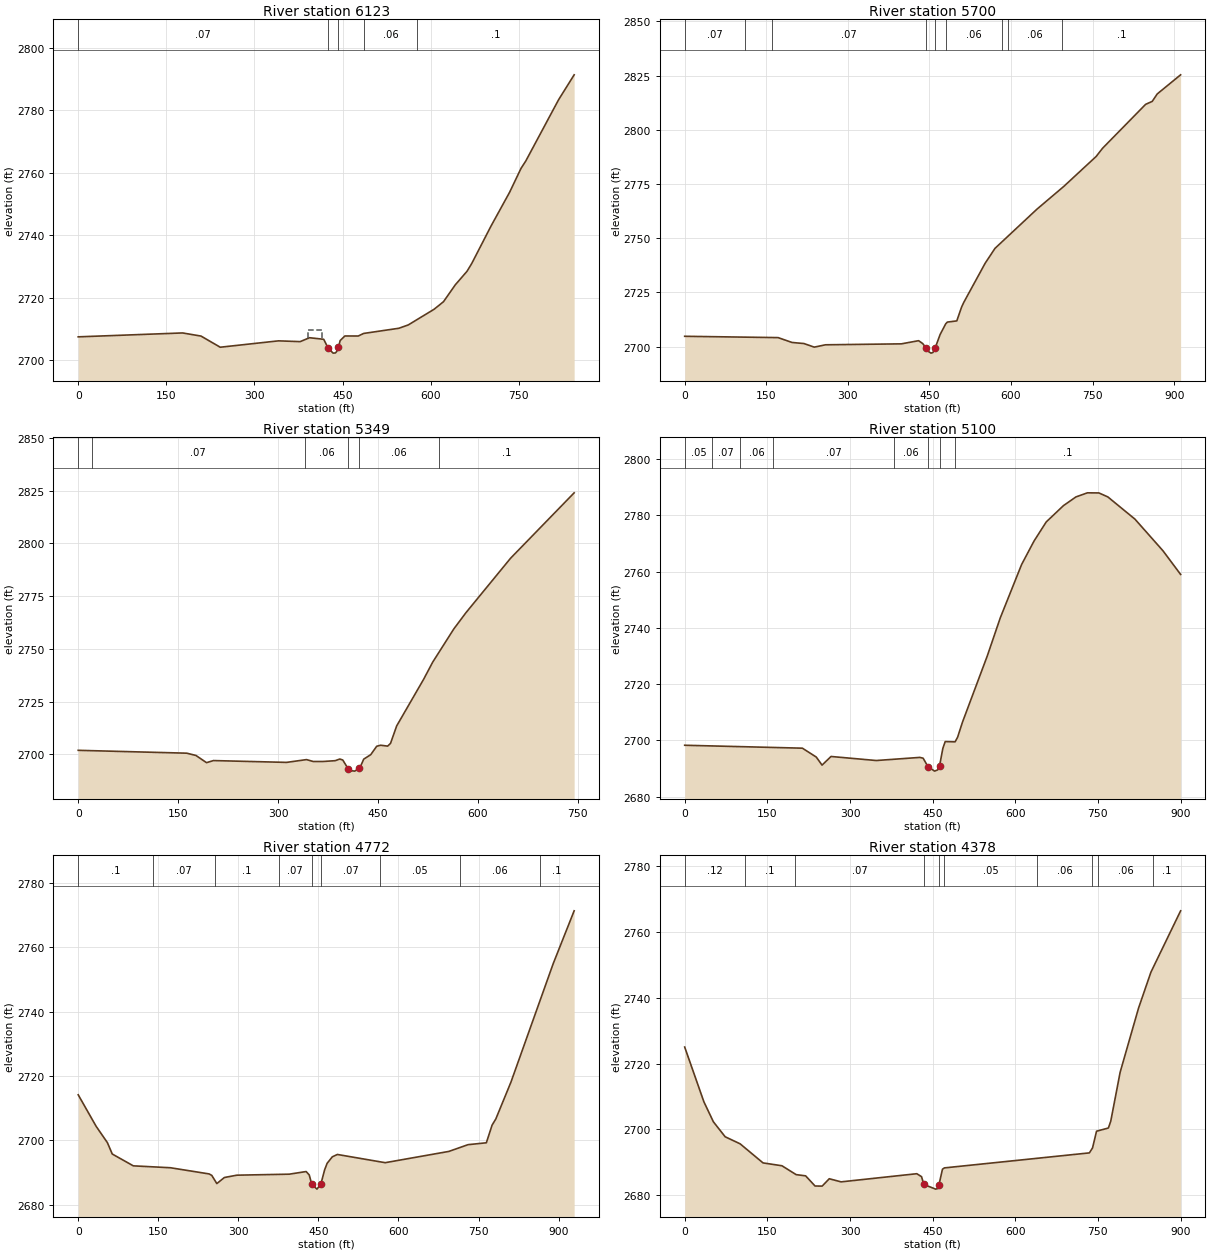
Type RM Length L Ch R = 1 ,6123    ,415,422.4,427.9
XS GIS Cut Line= 3
2315738.66865966540087.5942508872315758.74411778540563.929105596
2315755.71526002540931.580415627
#Sta/Elev= 30
       0  2707.5   177.7 2708.75   209.1 2707.75   241.8 2704.18     341 2706.22
   377.9 2705.97   393.9 2707.22     418 2706.72   425.5 2703.89     434 2702.29
     438 2702.35     442 2703.27   443.1 2704.13     446 2706.31     454 2707.78
   476.8 2707.77     486 2708.59     546 2710.25     562 2711.32     606 2716.34
     622 2718.76     642 2724.15     662 2728.49     670 2730.97   702.7 2742.91
   734.5 2753.78     754 2761.45     762 2763.78     818 2783.44   844.4 2791.38
#Mann= 5 ,-1,0
       0     .07       0   425.5    .045       0   443.1     .07       0
  486.76     .06       0  576.76      .1       0
#XS Ineff= 1 ,-1
  391.19  414.922709.643
Permanent Ineff=
       F
Bank Sta=425.5,443.1
XS Rating Curve= 0 ,0
Exp/Cntr(USF)=0,0
Exp/Cntr=0.3,0.1

Type RM Length L Ch R = 1 ,5700    ,350.3,351.2,351.6
XS GIS Cut Line= 3
2315543.55342636540033.3581075552315302.90355215540565.001671633
2315414.60720037540873.614993925
#Sta/Elev= 30
       0 2704.72   171.7 2704.11   197.4 2701.87   219.3 2701.37   238.2 2699.72
   258.9 2700.79   398.4 2701.23   430.1 2702.69   437.7 2701.35   443.3 2699.54
   447.7 2697.78   452.8 2696.95   456.4 2697.21   460.8 2699.51   469.6 2705.52
     480  2710.5     483 2711.28   500.3 2711.82   509.1 2718.19   513.2  2720.4
   552.5 2738.45   570.6 2745.31   647.6 2763.36   697.1 2773.89   756.5 2787.69
   768.4  2791.5   847.5 2811.75   859.6  2813.1   868.8 2816.54   911.8 2825.36
#Mann= 9 ,-1,0
       0     .07       0     110     .03       0     160     .07       0
   443.3    .045       0   460.8     .07       0     480     .06       0
  583.57      .1       0  593.57     .06       0  693.57      .1       0
Bank Sta=443.3,460.8
XS Rating Curve= 0 ,0
Exp/Cntr(USF)=0,0
Exp/Cntr=0.3,0.1

Type RM Length L Ch R = 1 ,5349    ,249,249,248.9
XS GIS Cut Line= 3
2315310.37294618539927.1962567962315075.41991816540239.836538556
2314913.99582383540554.115169808
#Sta/Elev= 30
       0 2701.93     163 2700.57   176.8 2699.48   192.6 2696.08     203 2697.07
   312.7 2696.21   342.7 2697.53   352.7 2696.64   367.7 2696.64   385.8 2697.02
   392.6  2697.8   397.1 2697.34405.22162693.161   409.3 2692.29   415.1 2692.07
421.2216 2693.34   424.1 2694.59   428.6 2697.76   439.1 2699.87     448 2703.85
   453.9 2704.34   464.5 2703.92   468.8 2705.23     478 2713.48   518.5  2735.6
     532 2743.66   563.8 2759.45     582 2767.14   648.9 2792.91   744.4 2823.93
#Mann= 6 ,-1,0
       0     .03       0      20     .07       0     340     .06       0
405.2216    .045       0421.2216     .06       0  541.08      .1       0
Bank Sta=405.2216,421.2216
XS Rating Curve= 0 ,0
Exp/Cntr(USF)=0,0
Exp/Cntr=0.3,0.1

Type RM Length L Ch R = 1 ,5100    ,326.5,328.1,330.7
XS GIS Cut Line= 2
2315049.37805381539738.0850054982314647.52737669540543.389937369
#Sta/Elev= 30
       0 2698.27   213.6 2697.23   238.8 2694.07   249.3 2691.21   265.6 2694.28
   347.7 2692.84   426.7 2693.95   432.7 2693.67   441.4 2690.71   453.5 2689.07
   459.4 2689.53   462.5  2690.9   468.5 2697.15   472.8 2699.58   490.7 2699.48
   495.2 2701.08   504.1 2706.46   549.2 2730.06   572.8 2743.61   611.4 2762.52
   633.8 2770.82   656.1 2777.67   687.4 2783.48     710 2786.57   730.9 2788.03
   751.7 2787.99   767.9 2786.58   817.1 2778.68     868 2767.42     900 2759.01
#Mann= 8 ,-1,0
       0     .05       0      50     .07       0     100     .06       0
     160     .07       0     380     .06       0   441.4    .045       0
   462.5     .06       0     490      .1       0
Bank Sta=441.4,462.5
XS Rating Curve= 0 ,0
Exp/Cntr(USF)=0,0
Exp/Cntr=0.3,0.1

Type RM Length L Ch R = 1 ,4772    ,396.8,394.3,391.4
XS GIS Cut Line= 4
 2314808.9074096539554.2238405522314743.99701279539706.771218271
2314561.66078654539981.3481236892314270.86949577540303.205545409
#Sta/Elev= 30
       0 2714.17    33.6 2704.38    54.7 2699.31    63.8 2695.78   103.2 2692.11
   172.7 2691.52   245.3  2689.6   250.3 2689.14   259.7  2686.6   273.9 2688.49
   297.2 2689.21   395.3 2689.52   427.1 2690.34   432.9 2689.27   437.6 2686.35
   447.3 2684.88   454.7 2686.48   461.7 2690.88   466.4  2692.9   476.1 2694.91
   485.6 2695.64   575.2 2693.09   694.5 2696.59   730.3 2698.68   764.7 2699.27
   775.5 2704.78   782.4 2706.65   810.7 2718.07     890 2754.91   929.2 2771.29
#Mann= 9 ,-1,0
       0      .1       0     140     .07       0  255.78      .1       0
  375.78     .07       0   437.6    .045       0   454.7     .07       0
  565.39     .05       0  715.39     .06       0  865.39      .1       0
Bank Sta=437.6,454.7
XS Rating Curve= 0 ,0
Exp/Cntr(USF)=0,0
Exp/Cntr=0.3,0.1

Type RM Length L Ch R = 1 ,4378    ,303.5,301.5,300.1
XS GIS Cut Line= 2
2314389.82808261 539380.650784522314063.45740533540219.389230647
#Sta/Elev= 30
       0 2725.06    34.9 2708.38    52.1 2702.31    73.5 2697.75   100.6 2695.61
   142.2  2689.8   176.5 2688.93   202.3 2686.23   219.5 2685.86   236.6 2682.77
   249.5 2682.74   262.4 2684.98   283.8 2684.03   421.2 2686.51   429.8 2685.62
   434.1 2683.23   455.5 2681.82   459.8 2682.02  461.562683.206   467.8 2687.87
   471.3 2688.28   734.5 2692.85   740.2 2694.38   747.4 2699.44   768.9 2700.42
   773.2 2702.48   790.3 2717.42   823.6 2736.88   846.1 2747.84     900 2766.51
#Mann= 10 ,-1,0
       0     .12       0     110      .1       0     200     .07       0
   434.1    .045       0  461.56     .07       0     470     .05       0
     640     .06       0     740     .05       0     750     .06       0
     850      .1       0
Bank Sta=434.1,461.56
XS Rating Curve= 0 ,0
Exp/Cntr(USF)=0,0
Exp/Cntr=0.3,0.1

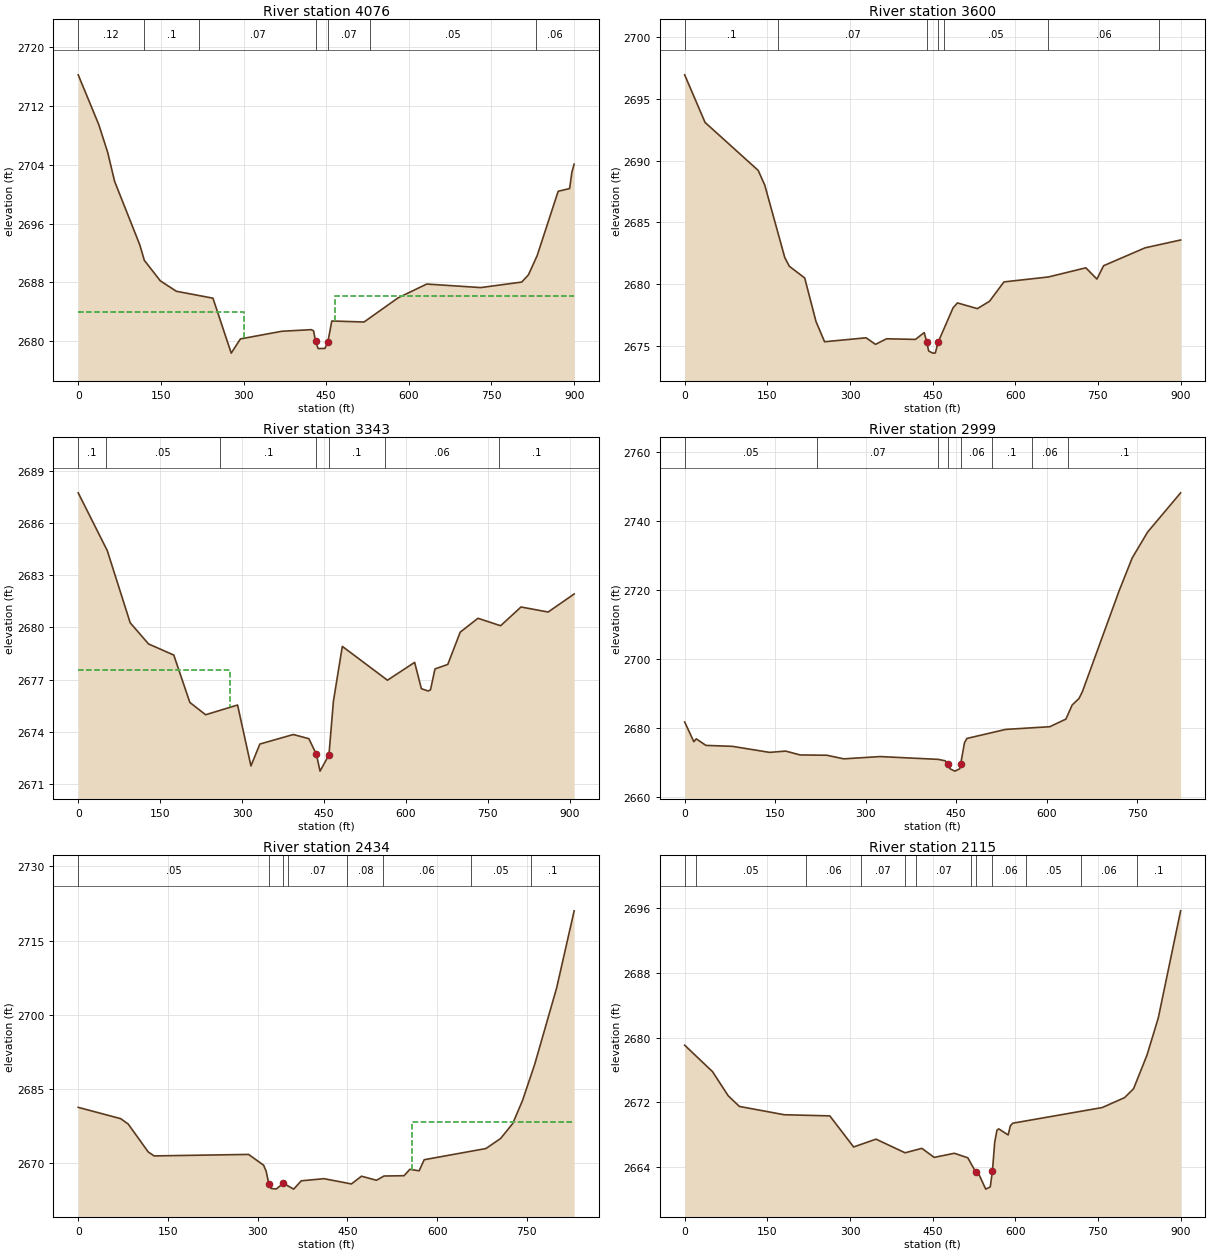
Type RM Length L Ch R = 1 ,4076    ,479.3,476.2,473.6
XS GIS Cut Line= 2
2314062.31246132539273.4787216142313823.16895607540141.125184119
#Sta/Elev= 30
       0 2716.21    37.3 2709.45    53.5 2705.67    66.1 2701.72   111.7 2693.11
     120 2690.99   149.1  2688.2   178.1 2686.79   244.5 2685.85   277.7 2678.38
   294.3 2680.31   369.3 2681.35   422.9 2681.57   427.1 2681.41   430.8 2679.97
   435.4    2679   447.8 2679.02  453.182679.934   460.2 2682.75   518.7 2682.61
   580.6  2685.9   632.5 2687.77   730.6 2687.29   804.9 2688.04   817.1 2689.03
   832.8 2691.62     871 2700.38   891.8 2700.75   895.9 2702.99     900 2704.06
#Mann= 7 ,-1,0
       0     .12       0     120      .1       0     220     .07       0
   430.8    .045       0  453.18     .07       0     530     .05       0
     830     .06       0
#XS Ineff= 2 , 0
             300    2684  465.35          2686.1
Permanent Ineff=
       F       F
Bank Sta=430.8,453.18
XS Rating Curve= 0 ,0
Exp/Cntr(USF)=0,0
Exp/Cntr=0.3,0.1

Type RM Length L Ch R = 1 ,3600    ,262.7,256.9,253.3
XS GIS Cut Line= 2
2313518.20182829 539220.38733006 2313433.2419302540116.368253806
#Sta/Elev= 30
       0 2696.94      37 2693.09   133.4 2689.21   145.4 2688.01   181.6 2682.17
   189.8 2681.46   217.8 2680.51   238.3 2676.99   253.9 2675.35   329.2 2675.67
   346.3 2675.14   366.4 2675.59   418.7 2675.54   434.7 2676.09   439.3 2675.32
   442.8  2674.6   450.3 2674.43   454.8 2674.44   460.3 2675.35     487 2678.09
     495 2678.49   531.2 2678.03   553.1 2678.62   579.4 2680.19     660 2680.59
     728 2681.33   748.1 2680.42   760.2  2681.5   835.7 2682.95     900 2683.58
#Mann= 7 ,-1,0
       0      .1       0     170     .07       0   439.3    .045       0
   460.3     .07       0     470     .05       0     660     .06       0
     860      .1       0
Bank Sta=439.3,460.3
XS Rating Curve= 0 ,0
Exp/Cntr(USF)=0,0
Exp/Cntr=0.3,0.1

Type RM Length L Ch R = 1 ,3343    ,336,344.3,347.5
XS GIS Cut Line= 4
2313263.14266977539238.5754177552313183.46271727539485.983573161
2313231.72818893539722.4843842742313338.11040502540115.161919388
#Sta/Elev= 30
       0 2687.76    53.2 2684.43    95.2 2680.27   128.8 2679.05     175 2678.41
   204.4 2675.68   233.3 2674.97   291.8 2675.53   316.3 2672.02   332.6 2673.28
   393.8 2673.83   422.4 2673.59   436.2 2672.68   442.8 2671.72   459.1 2672.65
   467.3 2675.75   483.6 2678.91   566.3 2676.96     616 2677.99   628.4 2676.47
   640.7 2676.34     645  2676.4   653.3 2677.61   676.7 2677.87   699.5 2679.73
     732 2680.53   773.5  2680.1   810.8 2681.18   860.5 2680.89   908.1 2681.93
#Mann= 7 ,-1,0
       0      .1       0      50     .05       0  259.92      .1       0
   436.2    .045       0   459.1      .1       0   561.3     .06       0
   771.3      .1       0
#XS Ineff= 2 , 0
          277.75 2677.57
Permanent Ineff=
       F       F
Bank Sta=436.2,459.1
XS Rating Curve= 0 ,0
Exp/Cntr(USF)=0,0
Exp/Cntr=0.3,0.1

Type RM Length L Ch R = 1 ,2999    ,561.3,565,567.4
XS GIS Cut Line= 3
2312984.18100883539365.9852481592312957.78334348539910.933108954
2312781.23160275540123.358411337
#Sta/Elev= 30
       0 2681.68    15.2 2675.95    19.2 2676.78    35.2 2674.88    79.3  2674.6
   140.6 2672.85   167.4 2673.22   191.4  2672.1   235.5 2672.02   263.5 2670.97
   323.9 2671.63     420 2670.82   431.7  2670.4436.09862669.548   439.7 2668.08
   447.7  2667.4   455.7 2668.06457.32862669.466   463.7 2675.68   467.7  2676.9
   531.8 2679.52   605.1 2680.31   631.7 2682.52   642.1 2686.62   653.4  2688.5
   659.1 2690.53   720.1 2719.89   741.5 2729.33     767 2736.85   821.8 2748.28
#Mann= 8 ,-1,0
       0     .05       0     220     .07       0     420     .06       0
436.0986    .045       0457.3286     .06       0     510      .1       0
  575.59     .06       0  635.59      .1       0
Bank Sta=436.0986,457.3286
XS Rating Curve= 0 ,0
Exp/Cntr(USF)=0,0
Exp/Cntr=0.3,0.1

Type RM Length L Ch R = 1 ,2434    ,314.7,319.2,316.2
XS GIS Cut Line= 3
2312699.59020658539153.545319089 2312511.6743983539750.782689972
  2312550.746002  539949.8618136
#Sta/Elev= 30
       0 2681.34    70.9 2679.06    83.5 2677.98     117 2672.34   126.8 2671.53
   284.8 2671.83   309.9 2669.66   314.1 2668.45   318.5 2665.94   322.5 2664.96
     331 2664.85     343    2666   360.2 2664.82   372.8  2666.5   410.7 2666.93
   456.7 2665.87   473.5 2667.43   498.6 2666.61   511.2 2667.47   544.7 2667.53
   554.3 2668.82   569.9 2668.52   578.3 2670.76   681.5 2673.02     706 2675.04
   726.4 2678.09   742.7 2682.73   763.1 2690.04   799.7 2705.45     829 2721.04
#Mann= 8 ,-1,0
       0     .05       0   318.5    .045       0     343     .05       0
     350     .07       0     450     .08       0     510     .06       0
   656.1     .05       0   756.1      .1       0
#XS Ineff= 2 , 0
                          558.14         2678.44
Permanent Ineff=
       F       F
Bank Sta=318.5,343
XS Rating Curve= 0 ,0
Exp/Cntr(USF)=0,0
Exp/Cntr=0.3,0.1

Type RM Length L Ch R = 1 ,2115    ,76.1,69.1,61.6
BEGIN DESCRIPTION:
structure xs 4
END DESCRIPTION:
XS GIS Cut Line= 2
2312520.34883418539071.4671878242312361.05475791539957.258019379
#Sta/Elev= 30
       0 2679.05    50.5 2675.78      79 2672.79    99.3 2671.47   180.7 2670.44
   263.4  2670.3   306.6 2666.45   347.2 2667.42     400 2665.73   430.4 2666.28
   452.8 2665.16   489.4 2665.67   513.8 2665.11   528.7 2663.29   534.1 2663.05
   546.3 2661.23   554.5  2661.5   558.5 2663.45   562.6 2667.02   566.7 2668.53
     570 2668.69     587 2667.94     591 2669.06   595.1 2669.39   757.7 2671.33
   798.3 2672.56   814.6 2673.66     839 2677.83   859.4 2682.41     900 2695.69
#Mann= 12 ,-1,0
       0     .07       0      20     .05       0     220     .06       0
     320     .07       0     400     .06       0     420     .07       0
     520     .06       0   528.7    .045       0   558.5     .06       0
     620     .05       0     720     .06       0     820      .1       0
Bank Sta=528.7,558.5
XS Rating Curve= 0 ,0
Exp/Cntr(USF)=0,0
Exp/Cntr=0.5,0.3

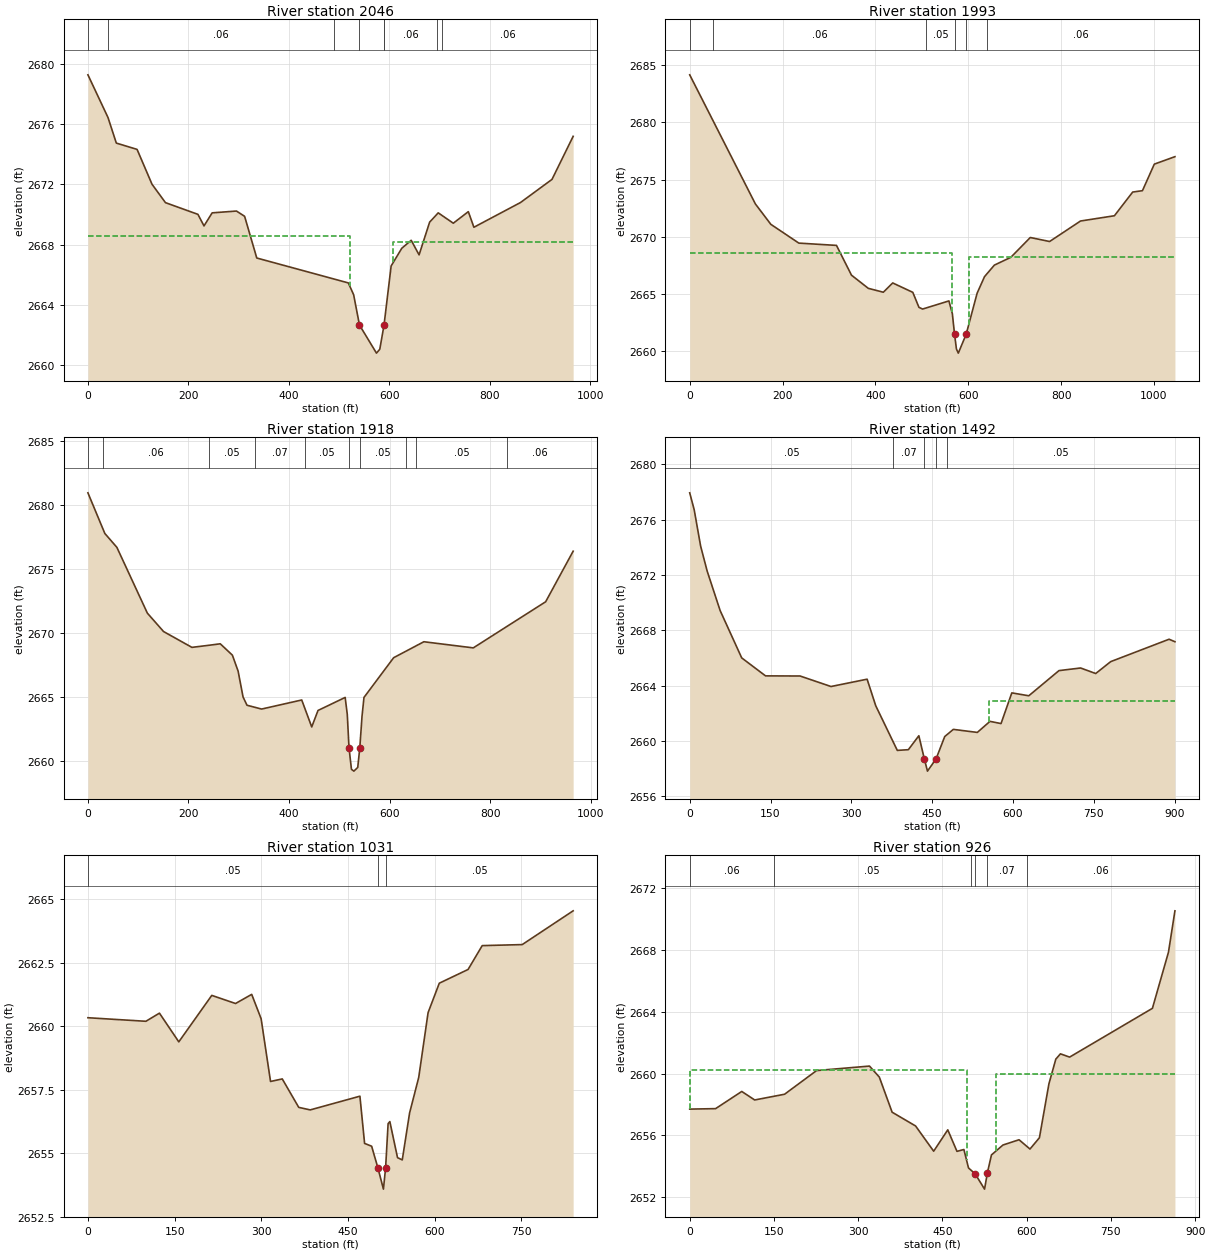
Type RM Length L Ch R = 1 ,2046    ,43.2,52.7,57.1
BEGIN DESCRIPTION:
structure xs 3; 19.2 ft between structure and xs
END DESCRIPTION:
XS GIS Cut Line= 5
2312454.89109928538996.2648795762312364.78363479 539654.93033108
2312318.04335203539778.2196518772312282.25933135539858.456171957
2312232.35381353539922.338787737
#Sta/Elev= 30
       0 2679.31      40 2676.46    56.5 2674.76    97.8 2674.34   127.5 2672.02
   154.3 2670.79   218.9 2670.01     231 2669.24   247.2 2670.11   295.6 2670.23
   311.8 2669.88     336  2667.1   518.2 2665.44   528.8 2664.65   540.4 2662.63
   574.2 2660.76   580.8 2661.02   589.2 2662.62   603.4 2666.57   624.6 2667.75
   643.3 2668.28     659 2667.31     680 2669.49   697.1 2670.11   727.1 2669.42
     757 2670.19   768.1 2669.15   860.9  2670.8   923.5 2672.34   965.6 2675.21
#Mann= 8 ,-1,0
       0     .07       0      40     .06       0     490     .07       0
   540.4    .045       0   589.2     .07       0     590     .06       0
   694.8     .05       0   704.8     .06       0
#XS Ineff= 2 , 0
             521  2668.6     608          2668.2
Permanent Ineff=
       F       F
Bank Sta=540.4,589.2
XS Rating Curve= 0 ,0
Exp/Cntr(USF)=0,0
Exp/Cntr=0.5,0.3

Type RM Length L Ch R = 1 ,1993    ,71.1,75,77.2
BEGIN DESCRIPTION:
structure xs 2; 16.1 ft between structure and xs
END DESCRIPTION:
XS GIS Cut Line= 4
2312420.48424014538947.9596832532312328.10187633539620.179191488
2312271.14861977539818.0676252762312171.04378049539943.921994371
#Sta/Elev= 30
       0 2684.15   141.5 2672.87   174.8 2671.09   235.1 2669.45   316.2 2669.25
   348.5 2666.65   384.7  2665.5   417.1 2665.16   437.3 2665.97   480.6 2665.15
   493.8 2663.84   501.7 2663.69   558.4  2664.4   565.8 2663.28   570.5  2661.5
   574.6  2660.2   578.6 2659.84   595.5 2661.48   619.2 2665.08   635.1 2666.52
   656.4 2667.53   691.8 2668.21   733.7 2669.94   775.3 2669.59   841.9 2671.38
   914.9 2671.84   954.3 2673.91   975.3 2674.03  1000.9 2676.35  1045.3    2677
#Mann= 6 ,-1,0
       0      .1       0      50     .06       0     510     .05       0
   570.5    .045       0   595.5     .05       0     640     .06       0
#XS Ineff= 2 , 0
             565  2668.6     601          2668.2
Permanent Ineff=
       F       F
Bank Sta=570.5,595.5
XS Rating Curve= 0 ,0
Exp/Cntr(USF)=0,0
Exp/Cntr=0.5,0.3

Type RM Length L Ch R = 1 ,1918    ,429.6,425.4,420.6
BEGIN DESCRIPTION:
structure xs 1
END DESCRIPTION:
XS GIS Cut Line= 4
2312379.05676847 538963.784126672312345.18882003539253.541075549
2312268.91745741539524.0660648282312185.09727813539907.251616498
#Sta/Elev= 30
       0 2680.98    33.6  2677.8    57.6 2676.71   118.2 2671.56   150.4 2670.12
   206.8 2668.88     240 2669.04   263.2 2669.16   287.3 2668.27   298.7 2667.02
   308.5    2665   316.3 2664.35   345.4 2664.05   425.2 2664.76   445.1 2662.65
   457.6 2663.94   511.6 2664.96   515.8 2663.63   519.2 2661.03   524.1 2659.33
   528.9 2659.19   536.6 2659.48   540.7 2661.02   545.1 2663.48     549 2664.96
     608 2668.07   668.1 2669.32   766.4 2668.84   910.3 2672.45     965 2676.41
#Mann= 10 ,-1,0
       0      .1       0      30     .06       0     240     .05       0
  331.73     .07       0  431.73     .05       0   519.2    .045       0
   540.7     .05       0   632.8     .06       0   652.8     .05       0
   832.8     .06       0
Bank Sta=519.2,540.7
XS Rating Curve= 0 ,0
Exp/Cntr(USF)=0,0
Exp/Cntr=0.3,0.1

Type RM Length L Ch R = 1 ,1492    ,462,461.3,458.3
XS GIS Cut Line= 4
 2311945.0142653538816.9063166082311919.73762544539153.434912115
2311919.73762544539416.8094611492311906.79200691539716.094316396
#Sta/Elev= 30
       0 2677.95     8.3 2676.73    20.3 2674.09    32.4 2672.29    56.4 2669.44
    96.5 2666.01   140.7 2664.71   204.8  2664.7   262.2 2663.94   329.2 2664.47
   345.2 2662.55   385.2 2659.32   405.7 2659.37   425.2 2660.38435.55552658.674
   441.2 2657.82   457.2 2658.71   473.2 2660.32   489.2 2660.84   533.7 2660.62
   557.2 2661.42   577.7 2661.26   597.7 2663.48   629.2 2663.27   685.2 2665.09
   725.3 2665.28   753.4 2664.88   781.2 2665.74   889.5 2667.36   900.4 2667.18
#Mann= 5 ,-1,0
       0     .05       0  377.48     .07       0435.5555    .045       0
   457.2     .07       0  477.48     .05       0
#XS Ineff= 2 , 0
                          555.49         2662.86
Permanent Ineff=
       F       F
Bank Sta=435.5555,457.2
XS Rating Curve= 0 ,0
Exp/Cntr(USF)=0,0
Exp/Cntr=0.3,0.1

Type RM Length L Ch R = 1 ,1031    ,105.7,105.2,103.5
BEGIN DESCRIPTION:
structure xs 4
END DESCRIPTION:
XS GIS Cut Line= 2
2311456.22530553538902.5856484392311612.21131356539727.905430965
#Sta/Elev= 30
       0 2660.34   100.3  2660.2   123.8 2660.52   157.3 2659.39   214.4 2661.22
   255.5  2660.9   283.5 2661.26   299.8  2660.3   316.1 2657.83   336.4 2657.93
   364.9 2656.81   384.8 2656.71   470.8 2657.25   478.9 2655.39   491.1 2655.28
     502 2654.42   511.5 2653.59   515.3 2654.44   519.6 2656.17   522.6 2656.25
   535.9 2654.83   544.1 2654.74   556.8 2656.59   572.6 2657.99   588.8 2660.54
   608.2  2661.7     658 2662.24   682.5 2663.18   751.7 2663.22   839.9 2664.55
#Mann= 3 ,-1,0
       0     .05       0     502    .045       0   515.3     .05       0
Bank Sta=502,515.3
XS Rating Curve= 0 ,0
Exp/Cntr(USF)=0,0
Exp/Cntr=0.5,0.3

Type RM Length L Ch R = 1 ,926     ,87,84.5,82.7
BEGIN DESCRIPTION:
structure xs 3; 15.4 ft between structure and xs
END DESCRIPTION:
XS GIS Cut Line= 2
2311336.48005826538900.1234101522311519.97872687539744.362874932
#Sta/Elev= 30
       0  2657.7    46.1 2657.73    92.7 2658.84   115.7 2658.29   168.9 2658.66
   225.9 2660.19   320.1 2660.48   337.6 2659.77   360.4  2657.5   402.2 2656.61
   434.4 2654.98   459.5 2656.36   475.9 2654.97   488.2 2655.09   496.4  2653.9
   508.4 2653.51     525 2652.53  530.122653.596   537.3 2654.74   557.8 2655.38
   586.4 2655.72   605.9 2655.12   622.7 2655.85   639.6 2659.33   651.9 2660.93
   660.1 2661.27   676.5 2661.06   823.9 2664.21   852.5 2667.84     864 2670.51
#Mann= 6 ,-1,0
       0     .06       0     150     .05       0     500     .07       0
   508.4    .045       0  530.12     .07       0     600     .06       0
#XS Ineff= 2 , 0
             493  2660.2   545.3            2660
Permanent Ineff=
       F       F
Bank Sta=508.4,530.12
XS Rating Curve= 0 ,0
Exp/Cntr(USF)=0,0
Exp/Cntr=0.5,0.3

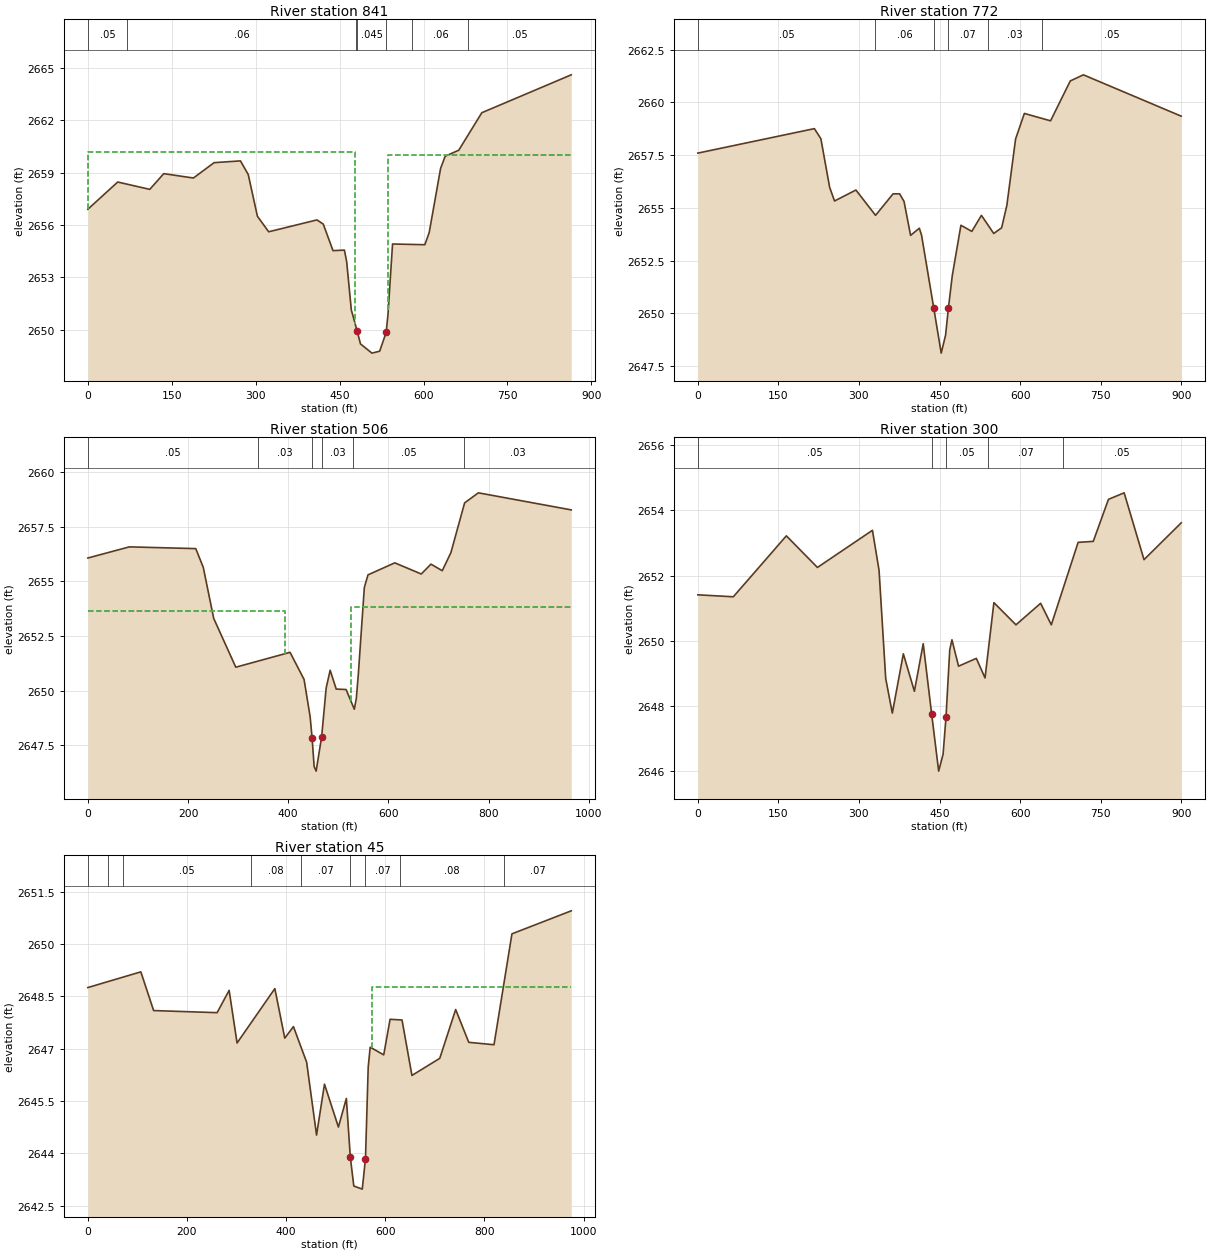
Type RM Length L Ch R = 1 ,841     ,68.1,69.3,79.2
BEGIN DESCRIPTION:
structure xs 2; 12.9 ft between structure and xs
END DESCRIPTION:
XS GIS Cut Line= 2
2311255.80063829538917.0239714952311439.29930691539761.263436275
#Sta/Elev= 30
       0  2656.9    53.4 2658.46   110.7 2658.04   135.7 2658.94   188.7 2658.69
   225.7 2659.57   272.8 2659.67   286.7 2658.89   303.1  2656.5   323.2 2655.61
   409.5 2656.29   420.8 2656.05   438.2 2654.53   458.6 2654.56   462.7 2653.88
   470.9 2651.14   481.3 2649.93   487.3 2649.19   507.7 2648.66   521.6 2648.77
   533.2 2649.85   536.4 2650.85   544.6 2654.91   602.3 2654.87   610.1 2655.56
   630.5 2659.24   638.7 2659.94   662.9 2660.28   704.2 2662.43     864  2664.6
#Mann= 7 ,-1,0
       0     .05       0      70     .06       0     480     .07       0
   481.3    .045       0   533.2     .07       0     580     .06       0
     680     .05       0
#XS Ineff= 2 , 0
             478  2660.2     537            2660
Permanent Ineff=
       F       F
Bank Sta=481.3,533.2
XS Rating Curve= 0 ,0
Exp/Cntr(USF)=0,0
Exp/Cntr=0.5,0.3

Type RM Length L Ch R = 1 ,772     ,263.7,266.3,268.6
BEGIN DESCRIPTION:
structure xs 1
END DESCRIPTION:
XS GIS Cut Line= 2
2311207.54069057538952.1065901942311376.38556982539836.126616409
#Sta/Elev= 30
       0 2657.59     217 2658.75   229.1 2658.27   245.4 2655.97   254.5 2655.32
   294.3 2655.84   330.9 2654.64   363.5 2655.66   375.7 2655.66   383.9  2655.3
   396.1 2653.69   412.4 2654.03   416.5  2653.7   439.1 2650.27   453.1 2648.11
   461.3 2648.97   466.5 2650.24   473.7 2651.78   489.8 2654.17   510.1 2653.88
     528 2654.64   550.9 2653.78   565.6 2654.05   575.3 2655.11   591.6 2658.26
   607.9 2659.47   656.7 2659.12   693.4 2661.01   717.8  2661.3     900 2659.34
#Mann= 6 ,-1,0
       0     .05       0     330     .06       0   439.1    .045       0
   466.5     .07       0     540     .03       0     640     .05       0
Bank Sta=439.1,466.5
XS Rating Curve= 0 ,0
Exp/Cntr(USF)=0,0
Exp/Cntr=0.3,0.1

Type RM Length L Ch R = 1 ,506     ,208.9,205.9,202.8
XS GIS Cut Line= 3
2310997.18461668538954.4661954622311036.25622039539523.795277986
  2311218.590371539873.579158752
#Sta/Elev= 30
       0 2656.06    82.9 2656.57   215.5 2656.49   230.5 2655.63   251.3  2653.3
   295.4 2651.07   403.7 2651.75   431.7 2650.51   443.8 2648.81   447.8 2647.82
   451.8 2646.53   455.8 2646.32   466.8 2647.89   475.8 2650.12   483.8 2650.93
   495.9 2650.07   515.6 2650.05     532 2649.15     536 2649.64     540 2650.74
     552 2654.71   559.3 2655.29   612.8 2655.84   665.7 2655.33     685 2655.78
   707.6 2655.48   724.9 2656.31   752.2 2658.58   779.7 2659.04   965.1 2658.26
#Mann= 6 ,-1,0
       0     .05       0     340     .03       0   447.8    .045       0
   466.8     .03       0     530     .05       0  750.67     .03       0
#XS Ineff= 2 , 0
          392.68 2653.64  524.92         2653.82
Permanent Ineff=
       F       F
Bank Sta=447.8,466.8
XS Rating Curve= 0 ,0
Exp/Cntr(USF)=0,0
Exp/Cntr=0.3,0.1

Type RM Length L Ch R = 1 ,300     ,254.6,254.6,254.6
XS GIS Cut Line= 2
2310720.49258531538956.8220701492310927.81322529539832.617795326
#Sta/Elev= 30
       0 2651.41    66.1 2651.35   164.8 2653.22   222.7 2652.25   325.1 2653.39
   337.4 2652.16   349.8 2648.84   362.1 2647.78   382.6  2649.6   403.2 2648.45
   419.6 2649.91   435.4 2647.74   448.4    2646   456.6 2646.52     462 2647.65
     469 2649.72   473.1 2650.03   485.4 2649.22   518.5 2649.46   534.7 2648.86
   551.2 2651.17   592.3 2650.49   638.2 2651.15   658.1 2650.49     708 2653.02
   736.2 2653.05   764.5 2654.34   793.7 2654.54   830.7 2652.49     900 2653.62
#Mann= 5 ,-1,0
       0     .05       0   435.4    .045       0     462     .05       0
     540     .07       0     680     .05       0
Bank Sta=435.4,462
XS Rating Curve= 0 ,0
Exp/Cntr(USF)=0,0
Exp/Cntr=0.3,0.1

Type RM Length L Ch R = 1 ,45      ,,,
XS GIS Cut Line= 3
2310575.74972383538956.7610705662310623.15776386539715.289711125
2310775.19044397539867.322391237
#Sta/Elev= 30
       0 2648.75   106.9  2649.2   132.7 2648.09   260.8 2648.03     285 2648.67
     301 2647.16   377.2 2648.72   397.2  2647.3   414.7 2647.63   441.3 2646.61
   461.3 2644.52   477.3 2645.98   505.4 2644.75   521.4 2645.57   529.4 2643.89
   536.4 2643.06   553.5 2642.97     560 2643.84   565.5 2646.47   569.5 2647.04
   596.8 2646.82   609.6 2647.84   633.7 2647.82   653.7 2646.23   709.8 2646.72
   741.9 2648.12   768.3 2647.18   819.2 2647.11   855.4 2650.29     975 2650.95
#Mann= 9 ,-1,0
       0     .05       0      40     .08       0      70     .05       0
     330     .08       0     430     .07       0   529.4    .045       0
     560     .07       0     630     .08       0  840.01     .07       0
#XS Ineff= 2 , 0
                          573.52         2648.77
Permanent Ineff=
       F       F
Bank Sta=529.4,560
XS Rating Curve= 0 ,0
Exp/Cntr(USF)=0,0
Exp/Cntr=0.3,0.1
LCMann Table=0

Chan Stop Cuts=-1
Use User Specified Reach Order=0
Composite Channel Slope=5